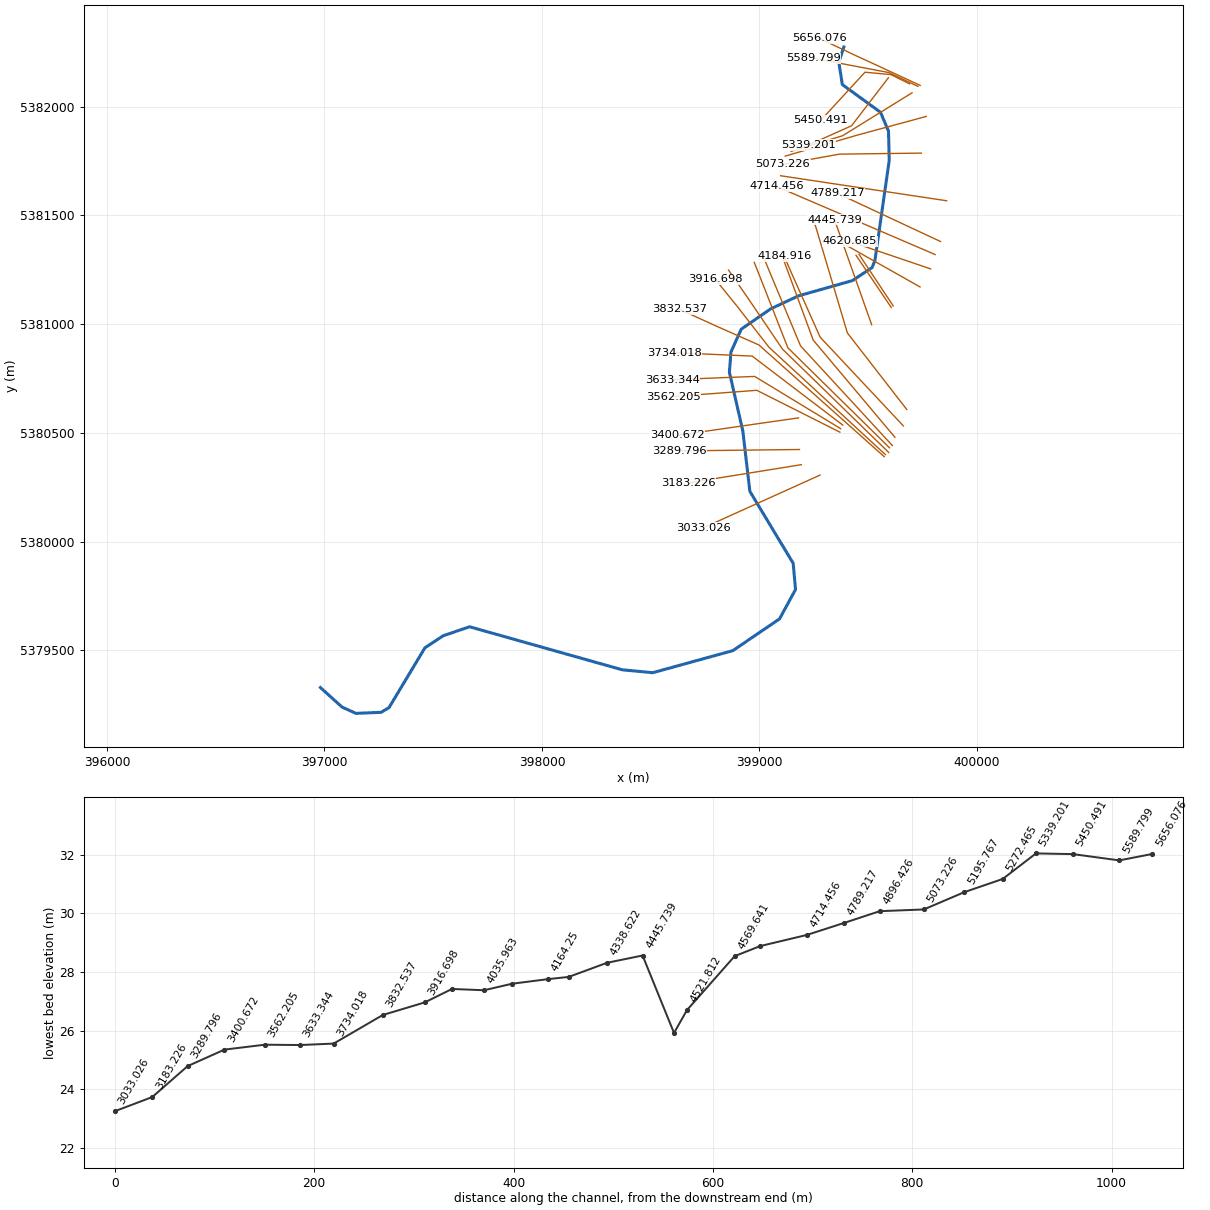
--- HarrysRiver.prj (project) ---

Proj Title=Harry's River
Current Plan=p05
Default Exp/Contr=0.3,0.1
SI Units
Geom File=g01
Flow File=f02
Plan File=p05
Y Axis Title=Elevation
X Axis Title(PF)=Main Channel Distance
X Axis Title(XS)=Station
BEGIN DESCRIPTION:
END DESCRIPTION:
DSS Export Rating Curves= 0
DSS Export Rating Curve Sorted= 0
DSS Export Volume Flow Curves= 0
DXF Filename=..\..\..\..\Special Apps\BlackDuck_Models\HEC-RAS (JK Jul15_11)\Ice Jam\Harry'sRiver.
DXF OffsetX= 0
DXF OffsetY= 0
DXF ScaleX= 1
DXF ScaleY= 10

--- HarrysRiver.p05 (plan) ---

Plan Title=Plan 05
Program Version=4.10
Short Identifier=Plan 05
Geom File=g01
Flow File=f02
Subcritical Flow
K Sum by GR= 0
Std Step Tol= 0.01
Critical Tol= 0.01
Num of Std Step Trials= 20
Max Error Tol= 0.3
Flow Tol Ratio= 0.001
Split Flow NTrial= 30
Split Flow Tol= 0.02
Split Flow Ratio= 0.02
Log Output Level= 0
Friction Slope Method= 1
Unsteady Friction Slope Method= 2
Unsteady Bridges Friction Slope Method= 1
Parabolic Critical Depth
Global Vel Dist= 0 , 0 , 0
Global Log Level= 0
CheckData=True
Encroach Param=-1 ,0,0, 0
Computation Interval=1HOUR
Output Interval=1HOUR
Run HTab= 0
Run UNet= 0
Run PostProcess= 0
Run WQNet= 0
UNET Theta= 1
UNET Theta Warmup= 1
UNET ZTol= 0.02
UNET ZSATol= 0.05
UNET MxIter= 20
UNET MaxInSteps= 0
UNET DtIC= 0
UNET DtMin= 0
UNET MaxCRTS= 20
UNET WFStab= 2
UNET SFStab= 1
UNET WFX= 1
UNET SFX= 1
UNET DSS MLevel= 4
UNET DZMax Abort= 100
UNET Convert EG Bridges= 0
UNET Use Existing IB Tables=-1
UNET Froude Reduction=False
UNET Froude Limit= 1
UNET Froude Power= 10
UNET Time Slicing=0,0, 5
UNET Junction Losses=0
Instantaneous Interval=1HOUR
Write IC File= 0
Write IC File at Sim End=0
Echo Input=False
Echo Parameters=False
Echo Output=False
Write Detailed= 0
WQ AD Non Conservative
WQ ULTIMATE=-1
WQ Max Comp Step=1HOUR
WQ Output Interval=15MIN
WQ Output Selected Increments= 0
WQ Output face flow=0
WQ Output face velocity=0
WQ Output face area=0
WQ Output face dispersion=0
WQ Output cell volume=0
WQ Output cell surface area=0
WQ Output cell continuity=0
WQ Output cumulative cell continuity=0
WQ Output face conc=0
WQ Output face dconc_dx=0
WQ Output face courant=0
WQ Output face peclet=0
WQ Output face adv mass=0
WQ Output face disp mass=0
WQ Output cell mass=0
WQ Output cell source sink temp=0
WQ Output cell source sink nsm=0
WQ Output MaxMinRange=-1
WQ Daily Max Min Mean=-1
WQ Daily Range=0
WQ Daily Time=0
WQ Create Restart=0
WQ Fixed Restart=0
WQ System Summary=0
WQ Use Fixed Temperature=0
Sorting and Armoring Iterations= 10
XS Update Threshold= 0.02
Hydraulics Update Threshold= 0.02
Energy Slope Method= 1
Volume Change Method= 0
XS Weighting Method= 0
Number of US Weighted Cross Sections= 1
Number of DS Weighted Cross Sections= 1
Upstream XS Weight=0.25
Main XS Weight=0.5
Downstream XS Weight=0.25
Number of DS XS's Weighted with US Boundary= 1
Upstream Boundary Weight= 1
Weight of XSs Associated with US Boundary= 0
Number of US XS's Weighted with DS Boundary= 1
Downstream Boundary Weight= 0.5
Weight of XSs Associated with DS Boundary= 0.5
Sediment Output Level= 4
Mass or Volume Output= 0
Output Increment Type= 1
Profile and TS Output Increment= 10
XS Output Flag= 0
XS Output Increment= 10
Disregard all LS=0
Disregard all Conn=0
Disregard all Breaches=0
Disregard all Pumps=0

--- HarrysRiver.f02 (steady flow) ---

Flow Title=ICESIM
Program Version=4.00
Number of Profiles= 1
Profile Names=PF 1
River Rch & RM=Harrys,BlackDuck       ,5656.076
    10.2
River Rch & RM=Harrys,BlackDuck       ,2545.527
    11.8
River Rch & RM=Harrys,BlackDuck       ,1503.609
    12.2
Boundary for River Rch & Prof#=Harrys,BlackDuck       , 1
Up Type= 0
Dn Type= 2
DSS Import GetInterval= 0
DSS Import GetPeak= 0
DSS Import FillOption= 0

--- HarrysRiver.g01 (geometry) ---

Geom Title=Updated_Geometry
Program Version=4.10

River Reach=Harrys          ,BlackDuck
Reach XY= 30
399388.055237579 5382274.1443354399364.9951644225382204.08508878
399381.0830854175382101.12239442399556.4414242435381974.02781858
399593.4436425265381887.15304521399596.6612267255381752.01450887
399530.7007506545381291.89996846399517.8304138585381259.72412648
399427.738056298 5381200.1988188399178.3752809035381129.41196643
399051.2807050555381069.88665876398916.142168714  5380976.576717
398869.0849998095380871.80413153 398861.84543536 5380778.8963878
 398923.381733165380509.82590918398955.9597731725380231.10267797
399155.0477954635379900.49590157399165.9071421335379779.83649411
399092.3049035895379644.69795777398877.5311583295379498.70007476
 398509.51996561 5379397.3461725 398369.555052975379410.61870732
397667.3173016175379608.50013554397546.6578941665379567.47593701
397462.1963089535379511.97260958397296.8929207465379236.86916059
397260.6950985125379215.15046725 397144.862067365379210.32409096
397080.9125814135379239.28234874396981.4833042315379329.13865456

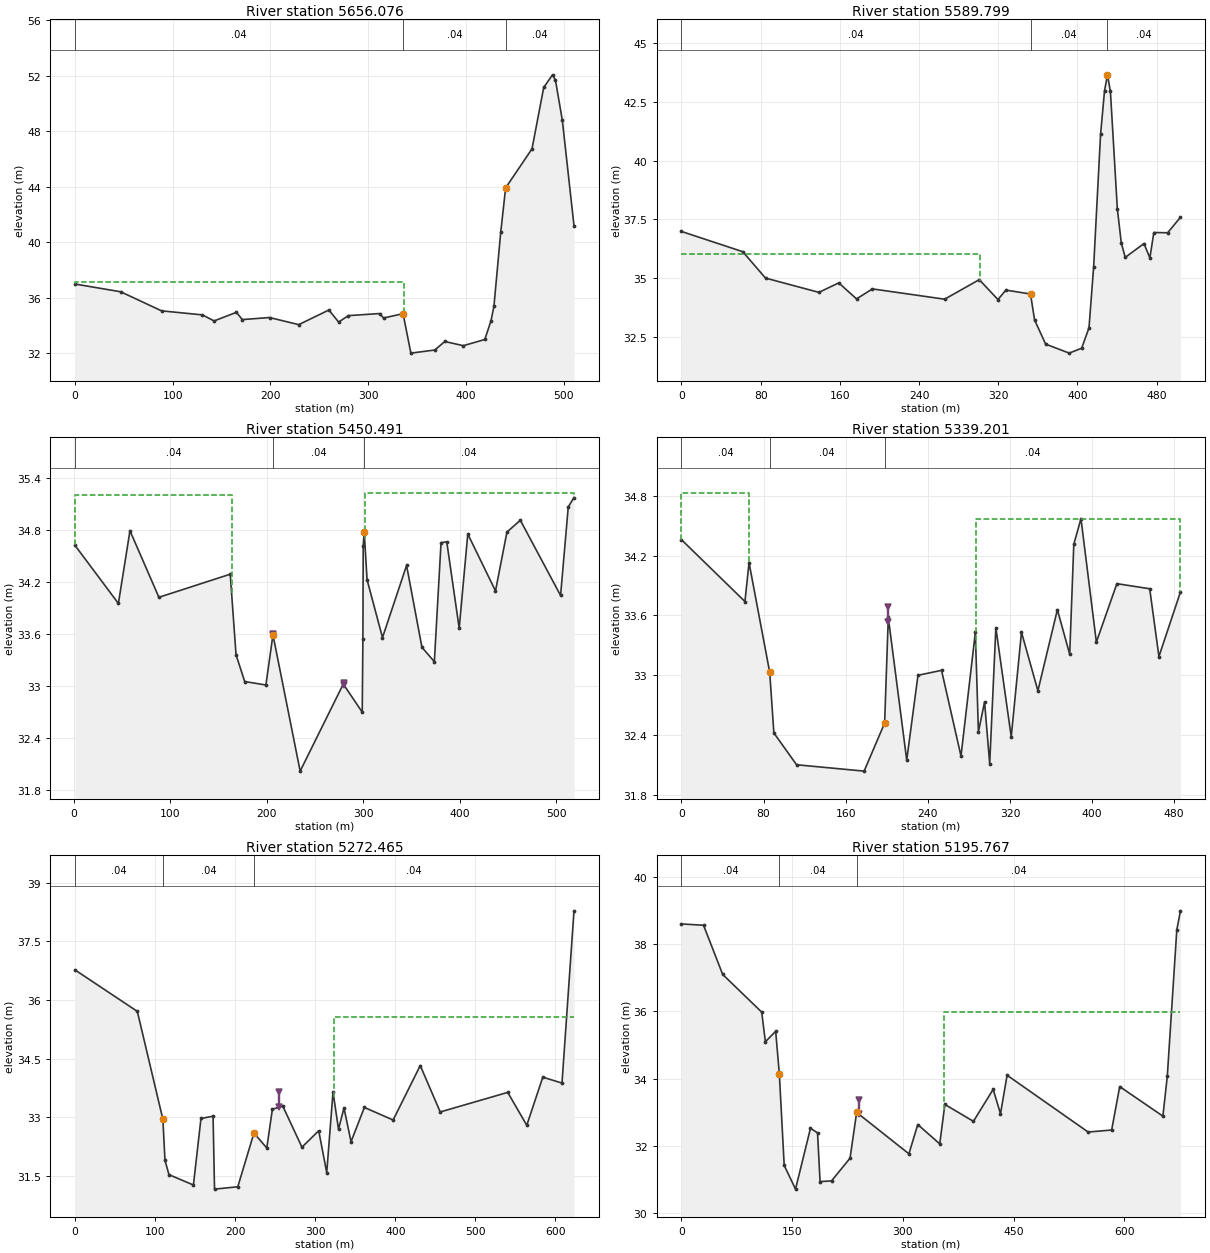
Type RM Length L Ch R = 1 ,5656.076,33.14,33.14,33.14
XS GIS Cut Line= 5
  399739.1953729 5382097.4348464  399509.7433094 5382203.7922077
  399445.4358793 5382233.2210316  399378.9485364 5382264.8297685
  399274.3127179 5382313.8778084
#Sta/Elev= 30
       0  36.996  46.764  36.438  88.555  35.065  130.37  34.773 142.318  34.339
 165.216  34.959  171.19  34.435 199.067  34.583 228.935  34.071 259.798  35.126
 269.754  34.256 279.723   34.72 311.703   34.87 315.703   34.55 335.693   34.86
 343.683   32.02 368.223  32.245378.3622  32.858397.3643  32.556419.3153  33.002
 425.643   34.34 428.643   35.38 435.633   40.73 440.633   43.92 467.623   46.73
 479.613   51.15 488.603   52.06 491.603   51.68 498.603   48.81 510.593    41.2
#Mann= 3 , 0 , 0
       0     .04       0 335.693     .04       0 440.633     .04       0
#XS Ineff= 2 , 0
          336.21   37.14
Permanent Ineff=
       F       F
Bank Sta=335.693,440.633
XS Rating Curve= 0 ,0
Exp/Cntr=0.3,0.1

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
Type RM Length L Ch R = 1 ,5589.799,46.437,46.437,46.437
XS GIS Cut Line= 3
  399728.6984304 5382093.1805761  399594.4743252 5382156.5932692
  399248.1537633 5382222.3214672
#Sta/Elev= 30
       0  36.986  61.938  36.123  84.914  34.999  138.86   34.39 158.859  34.795
 176.858  34.112 192.857  34.538 265.852  34.099 300.783  34.932 319.715  34.084
 327.686  34.487 352.594   34.32356.6828  33.216367.8553  32.186391.7003  31.801
404.2551  32.011411.6649  32.881 416.364   35.48 423.344   41.12 427.324   42.97
 430.314   43.66 433.304   42.95 440.284   37.95 444.264    36.5 448.254   35.88
 467.184   36.47 473.164   35.86 477.144   36.94 491.094   36.93 504.054   37.59
#Mann= 3 , 0 , 0
       0     .04       0 352.594     .04       0 430.314     .04       0
#XS Ineff= 2 , 0
          301.85   36.04
Permanent Ineff=
       F       F
Bank Sta=352.594,430.314
XS Rating Curve= 0 ,0
Exp/Cntr=0.3,0.1

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
Type RM Length L Ch R = 1 ,5450.491,37.097,37.097,37.097
XS GIS Cut Line= 4
  399690.6794986 5382104.4565188  399604.5671325 5382147.0241718
  399485.3025187 5382158.1209306   399281.942413 5381936.7528795
#Sta/Elev= 30
       1  34.623      46  33.952      58  34.792      88  34.023  161.97   34.29
  167.97   33.36  176.96   33.05  198.95   33.01206.2565   33.59234.4578  32.015
279.1855  33.021298.8249  32.696   299.5  33.538 299.848  34.621 300.847  34.779
 303.845  34.226 319.833  33.558 344.813  34.391 360.723  33.446 373.601  33.279
 380.535  34.654 386.479  34.664 399.356  33.666 408.272  34.754 436.999  34.097
 448.886  34.777  462.77  34.913 504.485  34.044 512.431  35.066 518.397  35.176
#Mann= 3 , 0 , 0
       1     .04       0206.2565     .04       0 300.847     .04       0
Levee=-1,206.17,33.6,-1,279.65,33.03,Levee 1,Levee 2
#XS Ineff= 2 , 0
          163.35   35.21  301.32           35.23
Permanent Ineff=
       F       F
Bank Sta=206.2565,300.847
XS Rating Curve= 0 ,0
Exp/Cntr=0.3,0.1

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
Type RM Length L Ch R = 1 ,5339.201,33.37,33.37,33.37
XS GIS Cut Line= 3
  399592.9469621 5382132.7318336  399423.5181942 5381911.9610149
  399225.4717901 5381823.2793945
#Sta/Elev= 30
       0   34.36   61.84   33.74   65.83   34.13   85.97   33.03 90.0309  32.422
112.1326  32.103177.9275  32.039   197.9   32.52  201.49   33.58  219.44   32.15
  230.41      33  253.35   33.05  272.31   32.19 286.283   33.43 289.281  32.433
 295.275  32.733 300.271  32.113 306.266  33.477 321.252  32.383 331.243  33.432
 347.229  32.845 366.212  33.658 378.202  33.211 382.198  34.314 389.192  34.571
 404.179  33.333 424.161  33.919 456.133  33.868 465.125  33.188 486.106  33.836
#Mann= 3 , 0 , 0
       0     .04       0   85.97     .04       0   197.9     .04       0
Levee=0,,,-1,201.32,33.69,,Levee 2
#XS Ineff= 2 , 0
           66.08   34.83  286.78           34.57
Permanent Ineff=
       F       F
Bank Sta=85.97,197.9
XS Rating Curve= 0 ,0
Exp/Cntr=0.3,0.1

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
Type RM Length L Ch R = 1 ,5272.465,38.35,38.35,38.35
XS GIS Cut Line= 3
  399701.6209694 5382063.4200661   399381.822275 5381865.8571436
  399145.8701921  5381794.457423
#Sta/Elev= 30
       0   36.77   77.85   35.71  109.79   32.95112.3739  31.905117.3627  31.538
 147.908  31.273157.3326  32.973172.4491  33.032174.2608  31.168203.3151  31.228
223.4968    32.6  239.55   32.22  246.53   33.21  259.51   33.29  283.46   32.24
  304.42   32.66   314.4   31.59 322.268  33.652 329.114    32.7  335.96  33.241
 344.761  32.379 361.425  33.256 397.318  32.934 431.218  34.326 456.144   33.14
 540.461   33.64 564.268    32.8 584.256  34.029 608.241  33.878 623.232   38.28
#Mann= 3 , 0 , 0
       0     .04       0  109.79     .04       0223.4968     .04       0
Levee=0,,,-1,255.33,33.66,,Levee 2
#XS Ineff= 2 , 0
                          323.17           35.57
Permanent Ineff=
       F       F
Bank Sta=109.79,223.4968
XS Rating Curve= 0 ,0
Exp/Cntr=0.3,0.1

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
Type RM Length L Ch R = 1 ,5195.767,40.847,40.847,40.847
XS GIS Cut Line= 3
  399766.6541816 5381954.7460617  399450.9005698 5381869.1759761
   399118.358117 5381772.4646533
#Sta/Elev= 30
       0    38.6   29.92   38.56   55.85    37.1  108.72   35.98   113.7    35.1
  127.67   35.41  132.65   34.13139.2053  31.427154.5325  30.721174.8124   32.53
184.3883  32.391187.7909  30.944203.3257  30.966228.4194   31.64  237.38      33
  308.19   31.77  320.16   32.64 349.953  32.066 356.895  33.237 395.572  32.735
 422.349  33.685 432.266   32.96 441.212  34.105  551.03  32.417 582.884  32.477
 593.793  33.767 652.303  32.889 658.254  34.071 671.146  38.425 676.104  38.989
#Mann= 3 , 0 , 0
       0     .04       0  132.65     .04       0  237.38     .04       0
Levee=0,,,-1,239.91,33.38,,Levee 2
#XS Ineff= 2 , 0
                          355.86           35.97
Permanent Ineff=
       F       F
Bank Sta=132.65,237.38
XS Rating Curve= 0 ,0
Exp/Cntr=0.3,0.1

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
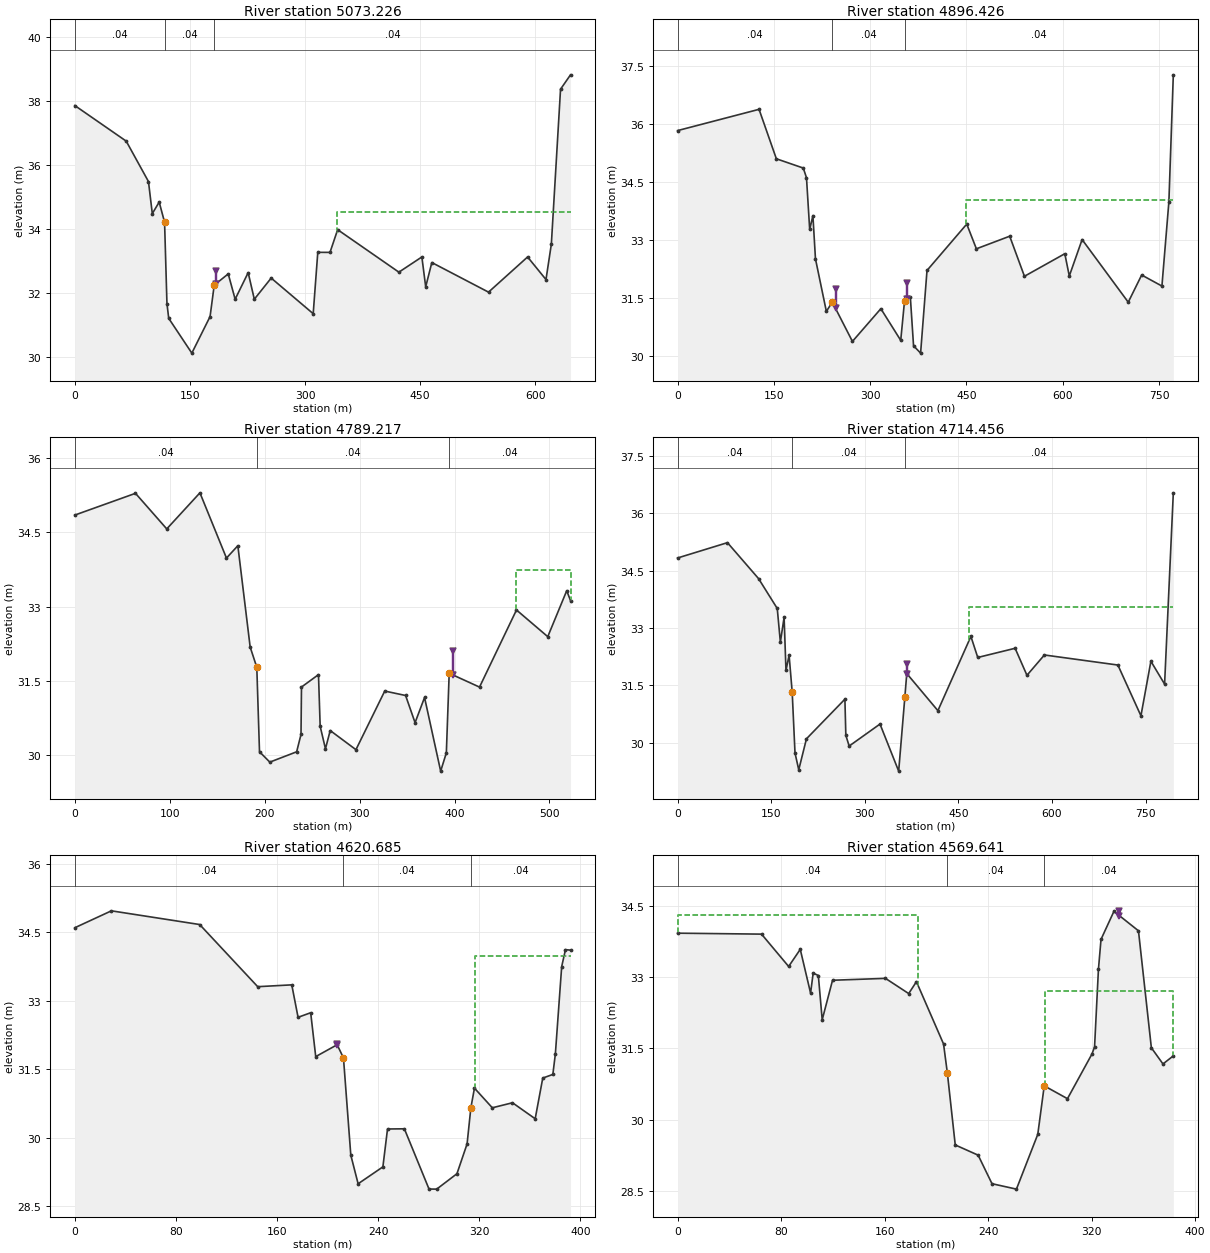
Type RM Length L Ch R = 1 ,5073.226,44.2,44.2,44.2
XS GIS Cut Line= 3
  399744.4060112   5381786.17299  399367.8225712  5381781.505881
  399106.6011423 5381734.1667912
#Sta/Elev= 30
       0   37.85   66.97   36.74   95.95   35.48  100.95   34.48  109.94   34.84
  116.94   34.21 120.035  31.675122.3531  31.214152.4639  30.129176.2272  31.269
  181.64   32.25   199.9    32.6  208.89   31.81  225.88   32.64  233.88   31.81
  255.87   32.47 310.609  31.359 316.581  33.272 332.505  33.271 342.458  33.979
 422.247  32.654 452.198  33.128  457.19  32.197 465.176  32.954 539.054  32.031
  589.97  33.128 613.931  32.423 620.919  33.528 632.899   38.36 645.878  38.808
#Mann= 3 , 0 , 0
       0     .04       0  116.94     .04       0  181.64     .04       0
Levee=0,,,-1,183.79,32.69,,Levee 2
#XS Ineff= 2 , 0
                          341.06           34.53
Permanent Ineff=
       F       F
Bank Sta=116.94,181.64
XS Rating Curve= 0 ,0
Exp/Cntr=0.3,0.1

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
Type RM Length L Ch R = 1 ,4896.426,35.737,35.737,35.737
XS GIS Cut Line= 3
  399860.7813797 5381567.1135712   399361.052084 5381642.4152451
  399097.1513195 5381682.1811142
#Sta/Elev= 30
       0   35.83  126.84   36.38  153.81    35.1  195.76   34.86  200.75   34.61
  205.74   33.27  210.74   33.63  214.73   32.51  231.71   31.15  240.96   31.39
272.3292  30.373  316.61   31.22  347.57    30.4  353.56   31.43  362.55   31.52
  367.54   30.26  378.53   30.07  388.52   32.21  450.44   33.41  465.42   32.77
 517.349  33.096  540.31  32.059 603.203  32.643 610.191  32.066 630.156  33.009
 702.033  31.388 722.948  32.092 754.501  31.806 765.347  33.986  772.25  37.273
#Mann= 3 , 0 , 0
       0     .04       0  240.96     .04       0  353.56     .04       0
Levee=-1,245.99,31.73,-1,357.36,31.89,Levee 3,Levee 2
#XS Ineff= 2 , 0
                          449.69           34.04
Permanent Ineff=
       F       F
Bank Sta=240.96,353.56
XS Rating Curve= 0 ,0
Exp/Cntr=0.3,0.1

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
Type RM Length L Ch R = 1 ,4789.217,37.38,37.38,37.38
XS GIS Cut Line= 2
   399832.543199 5381379.7150871  399358.1485343 5381601.3414919
#Sta/Elev= 30
       0   34.85    63.9   35.29   96.85   34.57  131.79    35.3  159.75   33.98
  171.73   34.23  184.71   32.18   191.7   31.77194.5463  30.062205.4178  29.852
233.6812  30.061238.2666  30.412238.7685  31.371256.6799  31.622258.4524  30.577
264.0253  30.122269.0393  30.491 296.139  30.104  326.48   31.29  348.45    31.2
  358.43   30.65  368.41   31.16  385.39   29.67  391.38   30.04  394.37   31.65
  426.32   31.37  465.26   32.93  498.21   32.39  518.18   33.32  522.17   33.12
#Mann= 3 , 0 , 0
       0     .04       0   191.7     .04       0  394.37     .04       0
Levee=0,,,-1,398.06,32.11,,Levee 2
#XS Ineff= 2 , 0
                           465.2           33.73
Permanent Ineff=
       F       F
Bank Sta=191.7,394.37
XS Rating Curve= 0 ,0
Exp/Cntr=0.3,0.1

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
Type RM Length L Ch R = 1 ,4714.456,46.885,46.885,46.885
XS GIS Cut Line= 3
  399807.7279263 5381319.8160248  399347.3608704 5381517.4829216
  399077.6742496 5381633.2777348
#Sta/Elev= 30
       0   34.83   79.84   35.23  129.74   34.29  159.68   33.51  164.67   32.63
  170.66   33.28  173.66   31.89  178.65   32.29  183.64   31.32188.1222  29.735
194.1288  29.295206.4487  30.104268.1115   31.14269.6093  30.197274.9122  29.915
  324.36   30.49   354.3   29.26  364.28   31.21  367.27   31.81  417.17   30.84
  470.07   32.78  481.05   32.23 540.939   32.47 559.906  31.764 587.859  32.295
 705.657  32.032 742.594  30.706 758.566  32.131 780.529  31.534 794.505  36.532
#Mann= 3 , 0 , 0
       0     .04       0  183.64     .04       0  364.28     .04       0
Levee=0,,,-1,367.93,32.05,,Levee 2
#XS Ineff= 2 , 0
                          466.61           33.55
Permanent Ineff=
       F       F
Bank Sta=183.64,364.28
XS Rating Curve= 0 ,0
Exp/Cntr=0.3,0.1

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
Type RM Length L Ch R = 1 ,4620.685,25.52,25.52,25.52
XS GIS Cut Line= 2
  399787.1910029 5381253.9270653  399415.0987584 5381380.0803342
#Sta/Elev= 30
       0    34.6   28.93   34.97   98.77   34.67  144.67   33.31  171.61   33.35
  176.59   32.64  186.57   32.74  190.56   31.78  207.52   32.04  212.51   31.75
218.3059  29.624224.0942  28.997243.6887  29.367247.3483  30.196260.6806    30.2
280.1786  28.882286.2658   28.88302.2671  29.217  310.29   29.87  313.28   30.66
  316.12   31.09  330.24   30.66  346.21   30.77  364.16   30.42  370.15   31.31
  378.13   31.39  380.13   31.84  385.12   33.75  388.11   34.12   392.1   34.11
#Mann= 3 , 0 , 0
       0     .04       0  212.51     .04       0  313.28     .04       0
Levee=-1,207.58,32.06,0,,,Levee 4,
#XS Ineff= 2 , 0
                          316.83           33.99
Permanent Ineff=
       F       F
Bank Sta=212.51,313.28
XS Rating Curve= 0 ,0
Exp/Cntr=0.3,0.1

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
Type RM Length L Ch R = 1 ,4569.641,47.83,47.83,47.83
XS GIS Cut Line= 2
  399738.4161068  5381170.924081  399402.3560773 5381360.5935163
#Sta/Elev= 30
       0   33.92   64.86    33.9   85.81   33.22   94.79   33.58  102.77   32.66
  104.77   33.08  108.76   33.03  111.75    32.1  119.74   32.93  160.65   32.97
  178.61   32.65  184.59    32.9  205.55   31.59  208.54   30.97214.5934  29.467
232.2958  29.252242.9922  28.652261.8988  28.538  278.39   29.69  283.38   30.71
  301.34   30.44   320.3   31.38  322.29   31.53  325.28   33.16  327.28   33.79
  337.26   34.38  356.22   33.97  366.19   31.51  375.17   31.17  383.16   31.34
#Mann= 3 , 0 , 0
       0     .04       0  208.54     .04       0  283.38     .04       0
Levee=0,,,-1,341.5,34.39,,Levee 5
#XS Ineff= 2 , 0
          186.08   34.31   283.7           32.71
Permanent Ineff=
       F       F
Bank Sta=208.54,283.38
XS Rating Curve= 0 ,0
Exp/Cntr=0.3,0.1

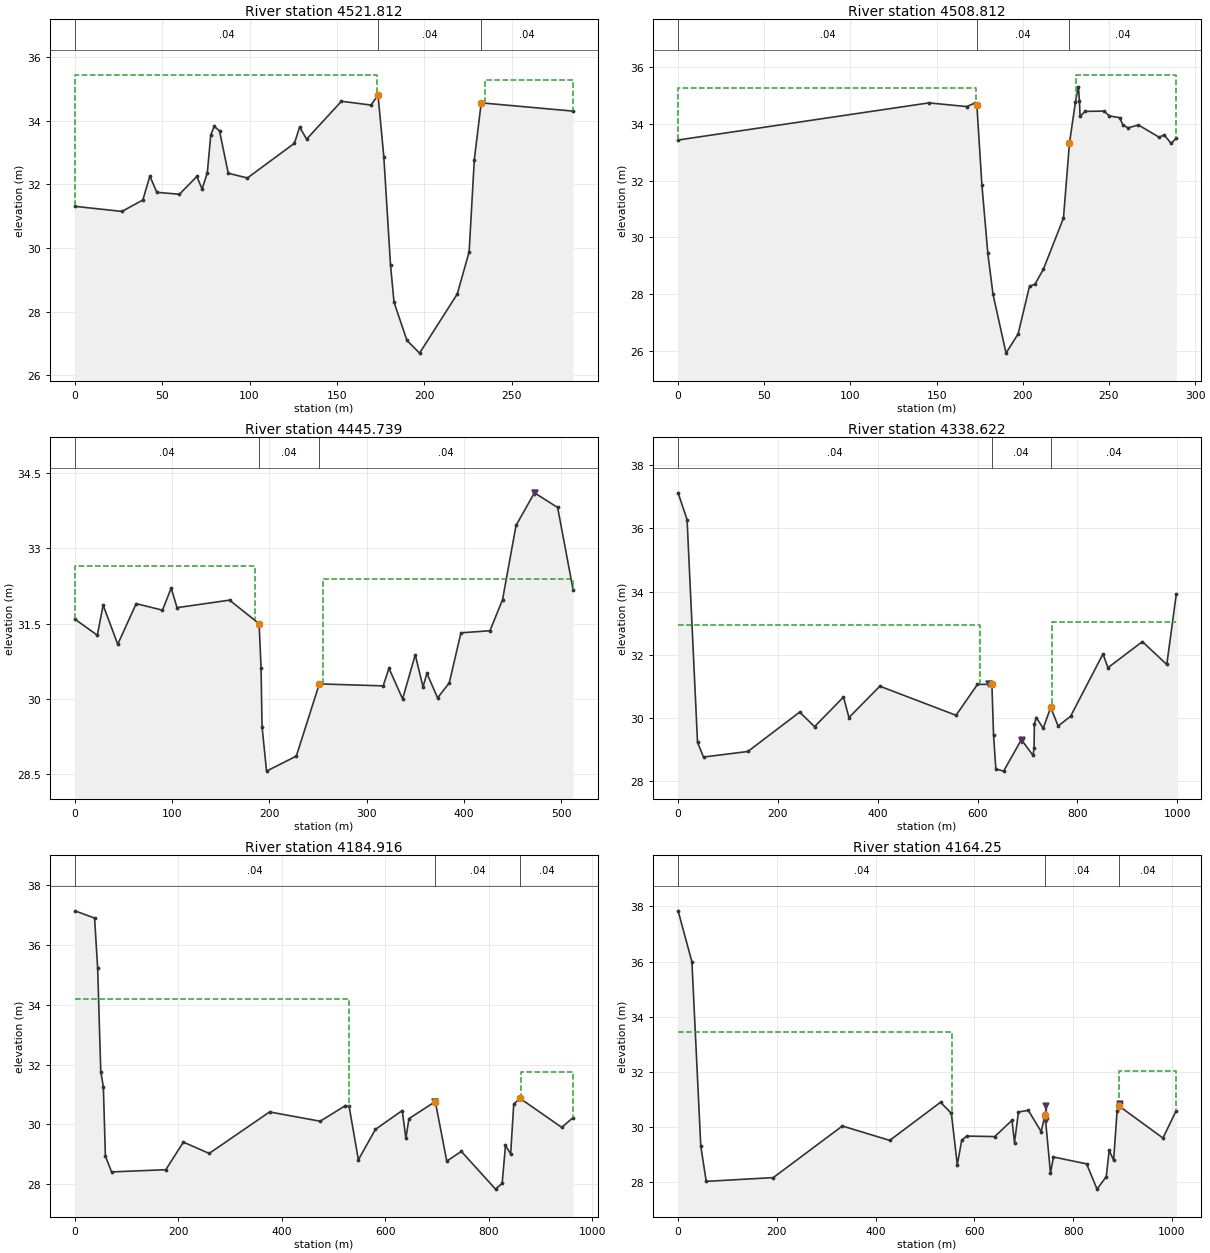
Type RM Length L Ch R = 1 ,4521.812,13,13,13
XS GIS Cut Line= 2
  399615.1057654  5381083.612182  399457.7461757 5381320.6717323
#Sta/Elev= 30
       0   31.31   26.93   31.15    38.9   31.51   42.89   32.26   46.88   31.75
   59.85   31.69   69.82   32.25   72.81   31.85   75.81   32.37    77.8   33.56
    79.8   33.82   82.79   33.68   87.78   32.35   98.75    32.2  125.68   33.29
  128.67    33.8  132.66   33.42  152.61   34.61  169.57   34.49  173.54   34.81
176.8621  32.875180.7319  29.452182.7148    28.3190.1075    27.1197.3631    26.7
218.9426  28.557225.7407  29.883228.7042  32.779232.6515   34.56  285.27    34.3
#Mann= 3 , 0 , 0
       0     .04       0  173.54     .04       0232.6515     .04       0
#XS Ineff= 2 , 0
          172.86   35.44  234.98           35.28
Permanent Ineff=
       F       F
Bank Sta=173.54,232.6515
XS Rating Curve= 0 ,0
Exp/Cntr=0.3,0.1

Type RM Length L Ch R = 1 ,4508.812,31.535,31.535,31.535
XS GIS Cut Line= 2
399605.7825261715381076.79698388399444.0550657475381316.39322155
#Sta/Elev= 30
       0   33.44  145.53   34.75  167.46   34.62172.2201  34.743  173.38   34.66
176.3061  31.842179.7353  29.437182.7282      28   190.3   25.92197.3134    26.6
203.9268  28.282207.0478  28.348211.9586   28.88223.6148  30.683 227.103   33.33
  230.59   34.79232.2812  35.319232.9129  34.803  233.25   34.28  236.24   34.45
  247.21   34.46   250.2   34.29  256.18   34.23  258.17   33.96  261.16   33.87
  267.14   33.97   279.1   33.54  282.09   33.62  286.08   33.32  289.07    33.5
#Mann= 3 , 0 , 0
       0     .04       0  173.38     .04       0 227.103     .04       0
#XS Ineff= 2 , 0
           172.6   35.29  230.75           35.74
Permanent Ineff=
       F       F
Bank Sta=173.38,227.103
XS Rating Curve= 0 ,0
Exp/Cntr=0.3,0.1

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
Type RM Length L Ch R = 1 ,4445.739,35.707,35.707,35.707
XS GIS Cut Line= 3
  399515.9338338 5380997.2168106   399384.155903 5381369.4466804
  399345.2075165 5381479.9542883
#Sta/Elev= 30
       0   31.59   22.99   31.27   28.99   31.87   43.99   31.09   62.98    31.9
   89.97   31.77   98.97   32.21  104.96   31.82  158.95   31.97  189.36    31.5
  191.36   30.62192.3676  29.448  197.01   28.56 227.633   28.86  251.25    30.3
  316.89   30.26  322.89   30.61  336.89      30  349.88   30.88  357.88   30.24
  361.88   30.51  372.87   30.02  384.87   30.32 396.856  31.318 426.683   31.36
 439.608  31.976 453.527   33.46 472.418   34.11 496.279  33.818 512.187  32.179
#Mann= 3 , 0 , 0
       0     .04       0  189.36     .04       0  251.25     .04       0
Levee=0,,,-1,473.13,34.11,,Levee 6
#XS Ineff= 2 , 0
          185.02   32.65  255.33            32.4
Permanent Ineff=
       F       F
Bank Sta=189.36,251.25
XS Rating Curve= 0 ,0
Exp/Cntr=0.3,0.1

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
Type RM Length L Ch R = 1 ,4338.622,38.428,38.428,38.428
XS GIS Cut Line= 5
  399677.2332826 5380607.5434294   399404.296548 5380959.3514561
  399266.5241644 5381422.2015179  399253.4467998 5381464.5434277
  399243.9831035 5381495.2823956
#Sta/Elev= 30
       0  37.129  17.964   36.28  38.923   29.22  50.899  28.757 139.723  28.933
 243.517   30.18 273.457  29.721 331.342  30.658 342.321   30.01 404.198  31.002
  556.87   30.08  599.78   31.06  628.72   31.06631.9362  29.471636.6008  28.381
 652.153  28.311687.7478  29.307711.0842   28.81713.1713  29.037713.7502  29.797
  717.54   30.01  731.51   29.67  746.47   30.33  761.44   29.74  786.39   30.05
  851.25  32.024 861.236  31.588 930.134  32.414 979.063   31.69 998.035  33.909
#Mann= 3 , 0 , 0
       0     .04       0  628.72     .04       0  746.47     .04       0
Levee=-1,623.79,31.08,-1,688.99,29.3,Levee 7,Levee 6
#XS Ineff= 2 , 0
          605.29   32.93  749.78           33.04
Permanent Ineff=
       F       F
Bank Sta=628.72,746.47
XS Rating Curve= 0 ,0
Exp/Cntr=0.3,0.1

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
Type RM Length L Ch R = 1 ,4184.916,20.67,20.67,20.67
XS GIS Cut Line= 4
  399661.7316799 5380531.9731161  399279.3354251 5380939.6794967
  399146.1183657   5381237.38687  399114.0554803 5381311.4130783
#Sta/Elev= 30
       0  37.143  37.934    36.9  43.924  35.226  49.913   31.76  54.905  31.259
  58.898   28.93  70.877  28.406 175.696   28.48 209.637  29.403 259.551  29.025
 376.347  30.413 474.177  30.102 523.092  30.626  530.08  30.603 548.049  28.813
  580.99   29.83  632.88   30.46  639.87   29.53  645.85   30.19  696.75   30.76
718.9758  28.767747.1401  29.092813.2122   27.83826.0547  28.025  832.48   29.29
  842.46   29.01  848.44   30.67  860.42   30.87 941.259  29.896 963.215  30.224
#Mann= 3 , 0 , 0
       0     .04       0  696.75     .04       0  860.42     .04       0
Levee=-1,696.04,30.76,0,,,Levee 7,
#XS Ineff= 2 , 0
           530.4    34.2  862.56           31.76
Permanent Ineff=
       F       F
Bank Sta=696.75,860.42
XS Rating Curve= 0 ,0
Exp/Cntr=0.3,0.1

Type RM Length L Ch R = 1 ,4164.25 ,36.31,36.31,36.31
XS GIS Cut Line= 4
  399622.9776731 5380479.6552069  399247.4127773 5380926.0958821
  399133.0388884 5381235.9335947  399105.4266585 5381310.0506328
#Sta/Elev= 30
       0   37.84  27.974   35.99  45.957  29.311  56.947  28.036  192.82  28.173
 332.689  30.043 428.598  29.521 531.501  30.902 553.481  30.503  565.47  28.641
 574.462  29.526 584.453  29.677 641.388   29.66 676.348   30.25 681.348   29.44
 689.338   30.55 709.308   30.61 735.278   29.84 743.268   30.44 754.258   28.33
 760.258   28.92827.3865   28.67848.5266  27.755867.2196  28.208 873.118   29.16
 882.108    28.8 889.103  30.583 893.098  30.768 981.995  29.6061008.964  30.601
#Mann= 3 , 0 , 0
       0     .04       0 743.268     .04       0 893.098     .04       0
Levee=-1,744.32,30.75,-1,894.45,30.83,Levee 7,Levee 8
#XS Ineff= 2 , 0
          554.01   33.45  893.39           32.05
Permanent Ineff=
       F       F
Bank Sta=743.268,893.098
XS Rating Curve= 0 ,0
Exp/Cntr=0.3,0.1

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
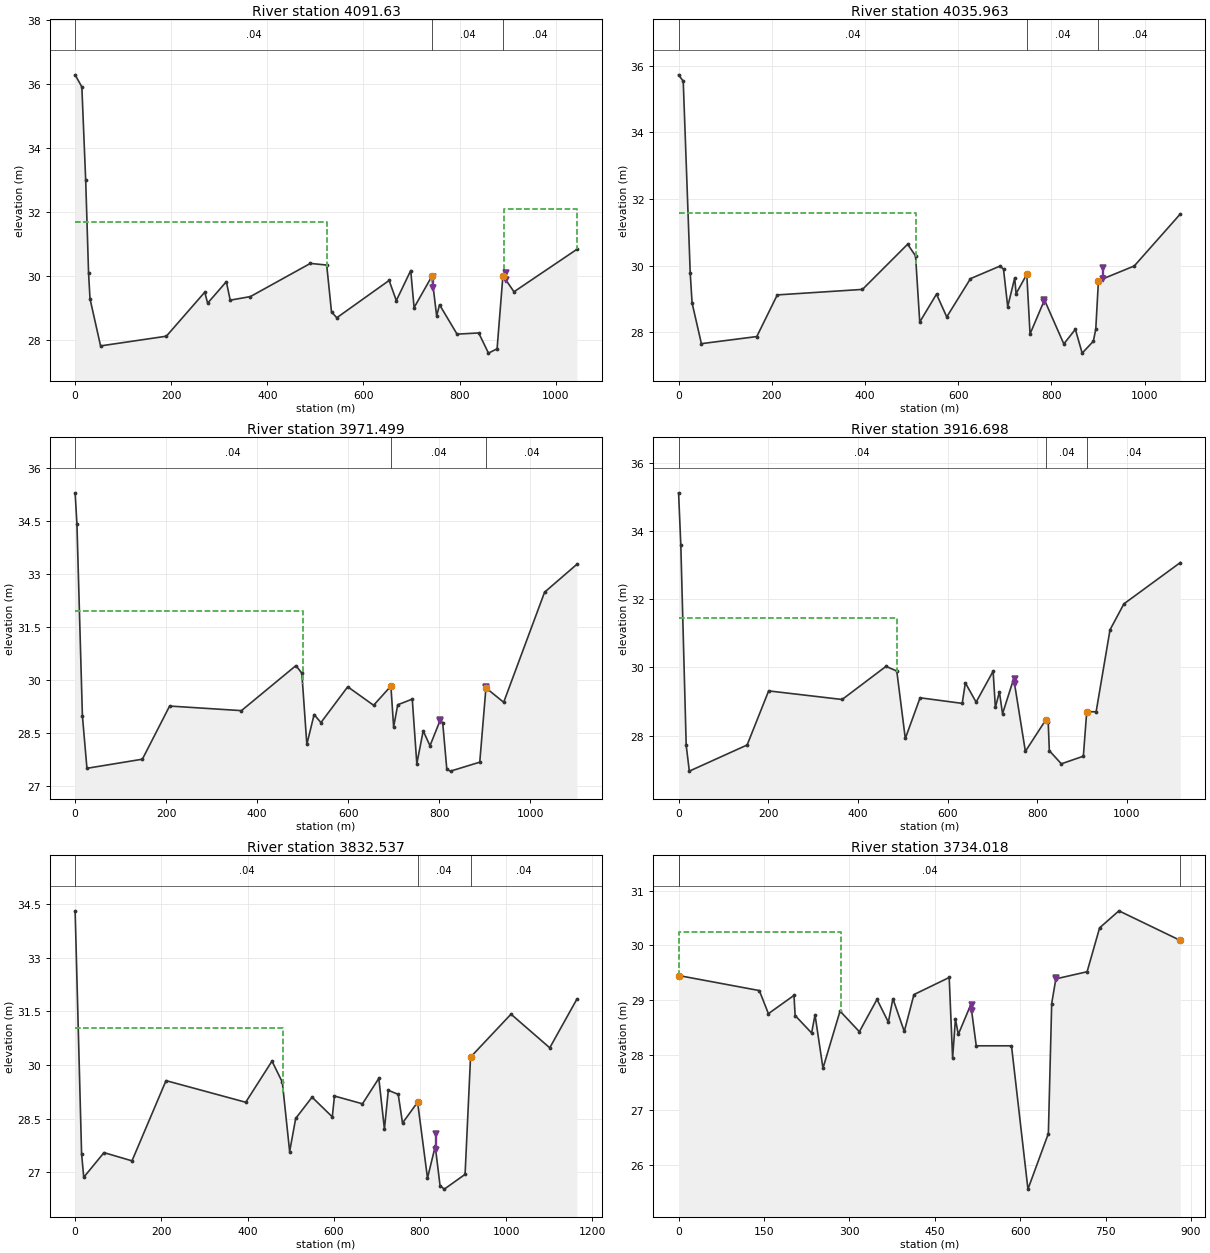
Type RM Length L Ch R = 1 ,4091.63 ,27.835,27.835,27.835
XS GIS Cut Line= 4
  399611.0049725 5380441.6379299  399189.0051211 5380899.8418945
  399055.5308747 5381219.3016668  399024.5276693   5381294.22608
#Sta/Elev= 30
       0    36.3  13.988  35.921  21.982  33.007  27.977  30.095  30.974  29.297
  52.956  27.823 189.841  28.126 269.774  29.503 275.769   29.16 314.737  29.832
  322.73  29.253 364.696  29.365 489.593  30.403 523.564  30.351 533.556  28.889
 544.546  28.703 653.463   29.87 668.453   29.24 698.433   30.18 705.433   29.02
 742.413      30 752.403   28.76 758.403   29.11794.8436  28.191 839.882  28.228
860.2638  27.597878.1909  27.733 890.317  30.022 913.303  29.5151044.223  30.843
#Mann= 3 , 0 , 0
       0     .04       0 742.413     .04       0 890.317     .04       0
Levee=-1,745.37,29.99,-1,896.56,30.09,Levee 7,Levee 8
#XS Ineff= 2 , 0
          524.41   31.71  893.39            32.1
Permanent Ineff=
       F       F
Bank Sta=742.413,890.317
XS Rating Curve= 0 ,0
Exp/Cntr=0.3,0.1

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
Type RM Length L Ch R = 1 ,4035.963,32.23,32.23,32.23
XS GIS Cut Line= 4
  399598.0869703 5380431.3035281  399130.6289389 5380891.0240988
  399009.0260665 5381200.5705635  398976.0851607 5381283.8916782
#Sta/Elev= 30
       0  35.722   9.991  35.531  24.978  29.779  28.974   28.88  48.956   27.66
 167.849  27.873 211.809  29.122 394.647  29.287 491.561  30.642 508.546  30.292
 517.538  28.308 553.505  29.146 575.485  28.462 626.438   29.61  690.36   29.99
  697.35   29.89  706.33   28.77  721.31   29.63  724.31   29.16  747.27   29.74
  754.26   27.95  785.21   28.97826.7367  27.652851.5236   28.09866.1131  27.376
890.0586  27.732895.3072  28.094 901.041   29.55 977.921   29.991076.771   31.55
#Mann= 3 , 0 , 0
       0     .04       0  747.27     .04       0 901.041     .04       0
Levee=-1,783.44,28.96,-1,910.31,29.94,Levee 7,Levee 8
#XS Ineff= 2 , 0
           509.6   31.58
Permanent Ineff=
       F       F
Bank Sta=747.27,901.041
XS Rating Curve= 0 ,0
Exp/Cntr=0.3,0.1

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
Type RM Length L Ch R = 1 ,3971.499,27.4,27.4,27.4
XS GIS Cut Line= 4
  399594.2115696 5380409.9888243  399106.0019672 5380884.9146096
  398950.8950563 5381114.0199483  398857.8854399 5381248.3671719
#Sta/Elev= 30
       0  35.305   3.995  34.408  15.979  28.992  25.967    27.5  147.81  27.758
 207.733  29.264 365.531  29.134 485.377   30.41  498.36  30.195 509.346  28.178
 525.326  29.024 540.306  28.795 599.231   29.81 656.158  29.286 694.132   29.83
 700.132   28.67 709.122    29.3 741.112   29.46 751.102   27.63 765.102   28.56
 780.092   28.14 802.082   28.85 808.082   28.78817.0861  27.467825.1957   27.42
889.4699  27.674 903.042   29.78 942.022   29.371031.982   32.491102.942   33.28
#Mann= 3 , 0 , 0
       0     .04       0 694.132     .04       0 903.042     .04       0
Levee=-1,801.41,28.88,-1,903.96,29.81,Levee 7,Levee 8
#XS Ineff= 2 , 0
          500.09   31.97
Permanent Ineff=
       F       F
Bank Sta=694.132,903.042
XS Rating Curve= 0 ,0
Exp/Cntr=0.3,0.1

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
Type RM Length L Ch R = 1 ,3916.698,42.08,42.08,42.08
XS GIS Cut Line= 4
  399578.7099668 5380400.3003226  399043.6577127 5380893.8479617
  398896.6394468 5381083.0167428   398795.879029 5381207.0295646
#Sta/Elev= 30
       0  35.112   4.998  33.572  16.993  27.715  23.991  26.961 152.941  27.727
 200.923  29.311 364.858  29.059 462.819   30.03  486.81  29.892 505.802  27.917
  538.79  29.109 632.756  28.945 639.753  29.547 663.744  28.982  701.73  29.888
 706.729  28.825 715.725  29.282 722.723  28.642 747.702   29.67 773.682   27.54
 819.628   28.47 824.628   28.39  827.13   27.56  853.92  27.175903.0036  27.398
 910.548    28.7 931.538    28.7 962.508    31.1 993.478   31.861119.368   33.07
#Mann= 3 , 0 , 0
       0     .04       0 819.628     .04       0 910.548     .04       0
Levee=-1,749.6,29.65,0,,,Levee 7,
#XS Ineff= 2 , 0
           487.4   31.44
Permanent Ineff=
       F       F
Bank Sta=819.628,910.548
XS Rating Curve= 0 ,0
Exp/Cntr=0.3,0.1

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
Type RM Length L Ch R = 1 ,3832.537,49.26,49.26,49.26
XS GIS Cut Line= 4
  399573.5427659 5380390.6118209  398997.5214702 5380904.1879699
  398803.6298304 5380990.0071264  398633.1122004 5381067.5151401
#Sta/Elev= 30
       0  34.30714.98804   27.5219.98401  26.86366.94604  27.552131.8929  27.322
 210.829  29.563 395.677  28.959 456.627  30.108 480.607  29.521 497.593   27.58
 511.581  28.507 549.551  29.101 596.514  28.551  601.51  29.133 666.458  28.916
 704.428  29.627 717.418  28.209 726.411  29.292 749.392  29.181 759.385  28.379
 794.359   28.96 817.318   26.84 835.295   27.73846.4414   26.63856.3089  26.532
904.4848  26.945 917.175   30.221011.035   31.421100.895   30.481163.805   31.84
#Mann= 3 , 0 , 0
       0     .04       0 794.359     .04       0 917.175     .04       0
Levee=-1,836.3,28.08,0,,,Levee 7,
#XS Ineff= 2 , 0
          483.17   31.03
Permanent Ineff=
       F       F
Bank Sta=794.359,917.175
XS Rating Curve= 0 ,0
Exp/Cntr=0.3,0.1

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
Type RM Length L Ch R = 1 ,3734.018,33.557,33.557,33.557
XS GIS Cut Line= 3
  399383.0186444 5380535.7919864  398966.6589635 5380852.9604536
  398607.2761958  5380868.577905
#Sta/Elev= 30
       0  29.451 141.767  29.177 157.741  28.756 202.668  29.089 204.664  28.722
 233.617  28.404 239.607  28.734 253.584  27.762 283.535  28.803 317.479  28.427
 348.428  29.016 368.395  28.602 376.382  29.029 396.349  28.432 413.321  29.104
 475.219  29.415 481.209  27.945   486.2  28.659 491.192  28.377 513.156  28.921
  522.73   28.17  584.62   28.17613.5134  25.558649.3722  26.571  655.23   28.94
  662.49   29.39  717.39   29.52  739.36   30.32   773.3   30.63  881.11   30.09
#Mann= 3 , 0 , 0
       0     .04       0       0     .04       0  881.11     .04       0
Levee=-1,514.54,28.92,-1,662.56,29.4,Levee 7,Levee 9
#XS Ineff= 2 , 0
          285.46   30.24
Permanent Ineff=
       F       F
Bank Sta=0,881.11
XS Rating Curve= 0 ,0
Exp/Cntr=0.3,0.1

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
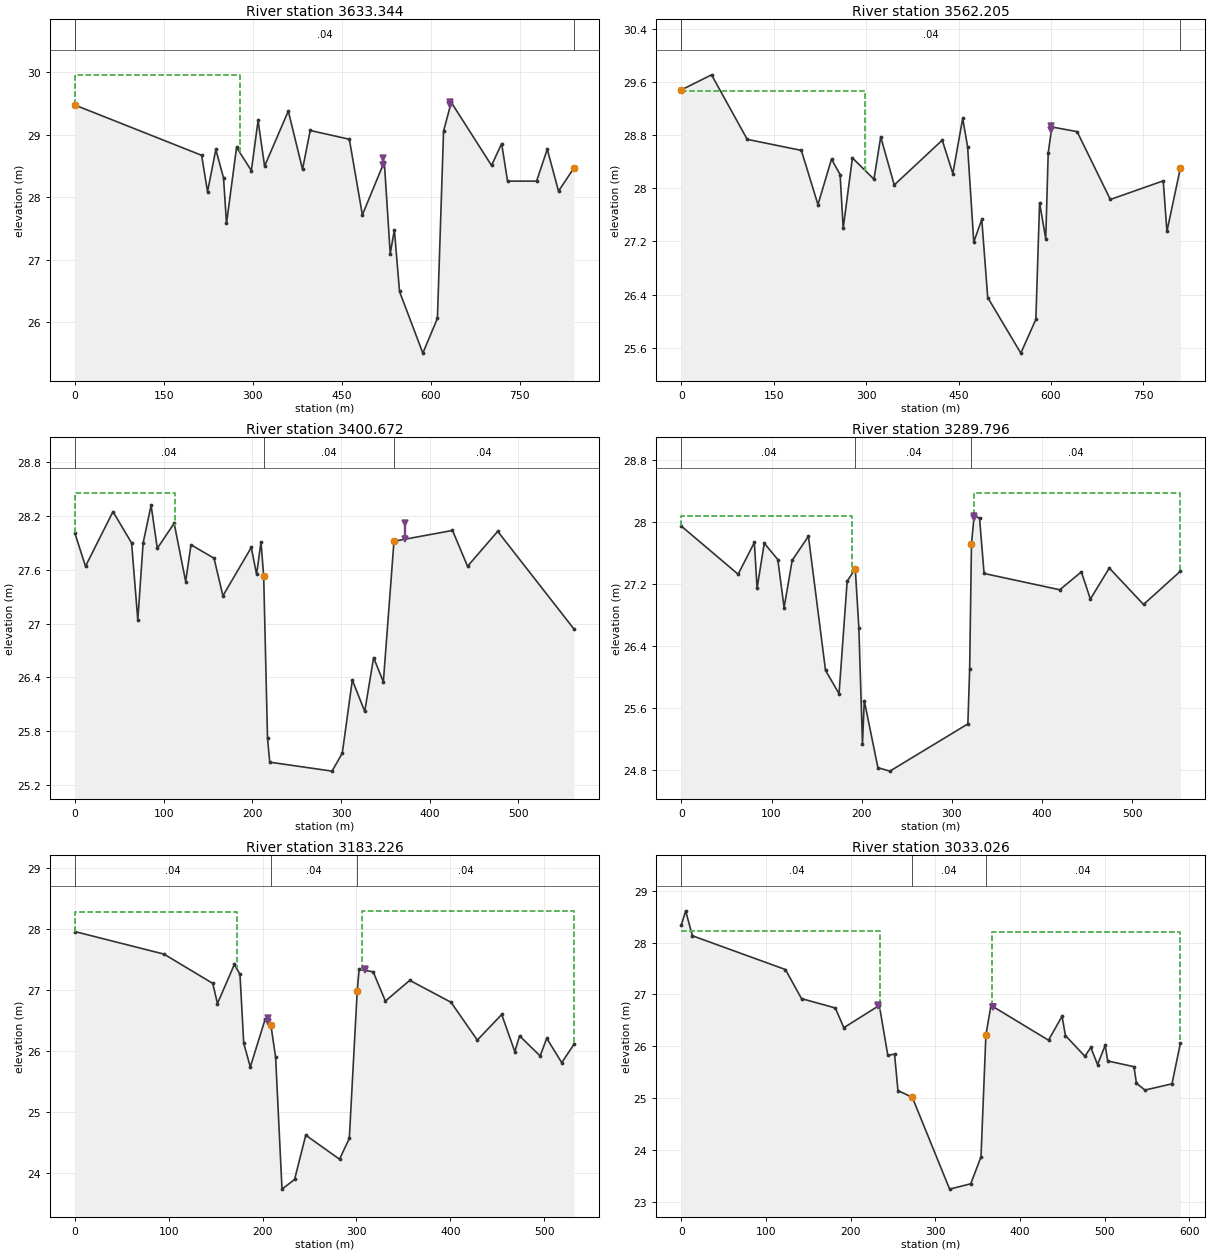
Type RM Length L Ch R = 1 ,3633.344,35.57,35.57,35.57
XS GIS Cut Line= 3
  399373.6550191 5380519.0905986  398978.0802206 5380759.5017056
  398599.5253944 5380744.5650832
#Sta/Elev= 30
       0  29.477  213.78  28.673  223.77   28.09 237.756  28.766 250.742  28.311
 255.737  27.583  272.72  28.799 297.694  28.428     309   29.23  319.99    28.5
  359.97   29.38  383.96   28.45  396.95   29.07  462.92   28.93  484.91   27.72
  521.89   28.57  531.88    27.1  538.88   27.48547.5781  26.495586.8938  25.509
611.4867  26.065  621.84   29.06  634.83   29.52   702.8   28.51  719.79   28.86
  729.79   28.26  778.76   28.26  796.75   28.77  815.74    28.1  841.73   28.47
#Mann= 3 , 0 , 0
       0     .04       0       0     .04       0  841.73     .04       0
Levee=-1,519.82,28.63,-1,633.48,29.53,Levee 7,Levee 9
#XS Ineff= 2 , 0
          278.41   29.96
Permanent Ineff=
       F       F
Bank Sta=0,841.73
XS Rating Curve= 0 ,0
Exp/Cntr=0.3,0.1

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
Type RM Length L Ch R = 1 ,3562.205,40.382,40.382,40.382
XS GIS Cut Line= 3
  399369.7289937 5380503.3025029  398987.8113788 5380695.6877634
  398604.6925953 5380667.0570696
#Sta/Elev= 30
       0  29.478  48.945  29.704  106.88  28.734 194.781  28.568  221.75  27.753
 243.725  28.437  257.71  28.204 262.704  27.397 277.687  28.455 312.648  28.135
 323.635  28.771  345.61  28.048 423.522  28.721  440.78   28.22  456.76   29.05
  464.75   28.62  474.74   27.19  487.72   27.53497.3899  26.356551.1455   25.52
575.5373  26.027  581.61   27.78   591.6   27.24   595.6   28.53  601.59   28.92
  642.54   28.85  696.48   27.83  782.38   28.11  788.37   27.35  810.35   28.31
#Mann= 3 , 0 , 0
       0     .04       0       0     .04       0  810.35     .04       0
Levee=0,,,-1,600.88,28.93,,Levee 9
#XS Ineff= 2 , 0
          298.68   29.46
Permanent Ineff=
       F       F
Bank Sta=0,810.35
XS Rating Curve= 0 ,0
Exp/Cntr=0.3,0.1

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
Type RM Length L Ch R = 1 ,3400.672,36.96,36.96,36.96
XS GIS Cut Line= 2
  399179.7051716 5380568.8802523  398622.5822001  5380488.930503
#Sta/Elev= 30
       0   28.01   11.99   27.64   42.96   28.25   63.94    27.9   70.93   27.04
   76.93    27.9   85.92   28.32   92.91   27.84   111.9   28.12  124.88   27.47
  130.88   27.88  156.85   27.73  166.84   27.31  198.81   27.85  204.81   27.55
   209.8   27.91   212.8   27.53217.1407  25.719219.6468  25.453289.8814  25.353
301.4159  25.554  312.71   26.37   326.7   26.02  336.69   26.62  347.68   26.35
  359.67   27.92  425.61   28.04  442.59   27.64  476.56   28.03  562.48   26.94
#Mann= 3 , 0 , 0
       0     .04       0   212.8     .04       0  359.67     .04       0
Levee=0,,,-1,371.63,28.12,,Levee 9
#XS Ineff= 2 , 0
           112.6   28.46
Permanent Ineff=
       F       F
Bank Sta=212.8,359.67
XS Rating Curve= 0 ,0
Exp/Cntr=0.3,0.1

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
Type RM Length L Ch R = 1 ,3289.796,35.523,35.523,35.523
XS GIS Cut Line= 2
  399184.0649974 5380423.5527267  398631.1392088  5380417.051633
#Sta/Elev= 30
       0   27.95   62.96   27.33   80.95   27.74   83.95   27.15   91.95   27.73
  106.94   27.52  113.93    26.9  122.93   27.51  140.92   27.82   159.9   26.09
   174.9   25.79  183.89   27.24  192.89    27.4  196.88   26.64  200.88   25.14
  202.88    25.7218.0375  24.835 231.289  24.791  317.81    25.4  319.81   26.11
  321.81   27.72  324.81   28.09   330.8   28.05   335.8   27.34  419.75   27.13
  443.74   27.36  453.73   27.01  474.72   27.41   512.7   26.94  553.67   27.37
#Mann= 3 , 0 , 0
       0     .04       0  192.89     .04       0  321.81     .04       0
Levee=0,,,-1,324.58,28.08,,Levee 9
#XS Ineff= 2 , 0
          189.78   28.08  325.11           28.38
Permanent Ineff=
       F       F
Bank Sta=192.89,321.81
XS Rating Curve= 0 ,0
Exp/Cntr=0.3,0.1

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
Type RM Length L Ch R = 1 ,3183.226,37.55,37.55,37.55
XS GIS Cut Line= 2
  399192.7846489 5380353.7955144  398673.3968344 5380270.1265934
#Sta/Elev= 30
       0   27.96   94.94   27.59   146.9   27.11   151.9   26.78  169.89   27.42
  175.88   27.26  179.88   26.13  186.88   25.74  202.87   26.53  208.86   26.42
  213.86    25.9220.6486  23.736234.0616  23.894245.9488  24.621 281.916  24.227
 292.356  24.567   300.8   26.99   302.8   27.34  317.79    27.3  330.78   26.82
  356.77   27.16  400.74    26.8  428.72   26.18   454.7    26.6   468.7   25.99
  473.69   26.25  495.68   25.92  502.67   26.21  518.66   25.81  531.65   26.11
#Mann= 3 , 0 , 0
       0     .04       0  208.86     .04       0   300.8     .04       0
Levee=-1,206.17,26.54,-1,309.25,27.35,Levee 10,Levee 9
#XS Ineff= 2 , 0
          172.33   28.28  305.55            28.3
Permanent Ineff=
       F       F
Bank Sta=208.86,300.8
XS Rating Curve= 0 ,0
Exp/Cntr=0.3,0.1

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
Type RM Length L Ch R = 1 ,3033.026,38.903,38.903,38.903
XS GIS Cut Line= 2
   399278.527889  5380305.837431  398742.3802679 5380063.6471846
#Sta/Elev= 30
       0   28.34       5   28.61   12.99   28.13  122.91   27.48  141.89   26.92
  181.86   26.74  191.86   26.36  233.82   26.79  243.82   25.83  251.81   25.85
  255.81   25.15  272.79   25.02316.8579  23.253341.8358  23.356353.9215  23.874
  359.73   26.22  365.72   26.79  433.67   26.12  449.66   26.58  453.66   26.21
  476.64   25.81  483.63   25.98  491.63   25.65  500.62   26.02  503.62   25.72
   534.6   25.61  537.59   25.29  547.59   25.16  579.56   25.28  589.56   26.07
#Mann= 3 , 0 , 0
       0     .04       0  272.79     .04       0  359.73     .04       0
Levee=-1,232.07,26.79,-1,368.46,26.76,Levee 10,Levee 9
#XS Ineff= 2 , 0
          234.71   28.22  366.34            28.2
Permanent Ineff=
       F       F
Bank Sta=272.79,359.73
XS Rating Curve= 0 ,0
Exp/Cntr=0.3,0.1

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