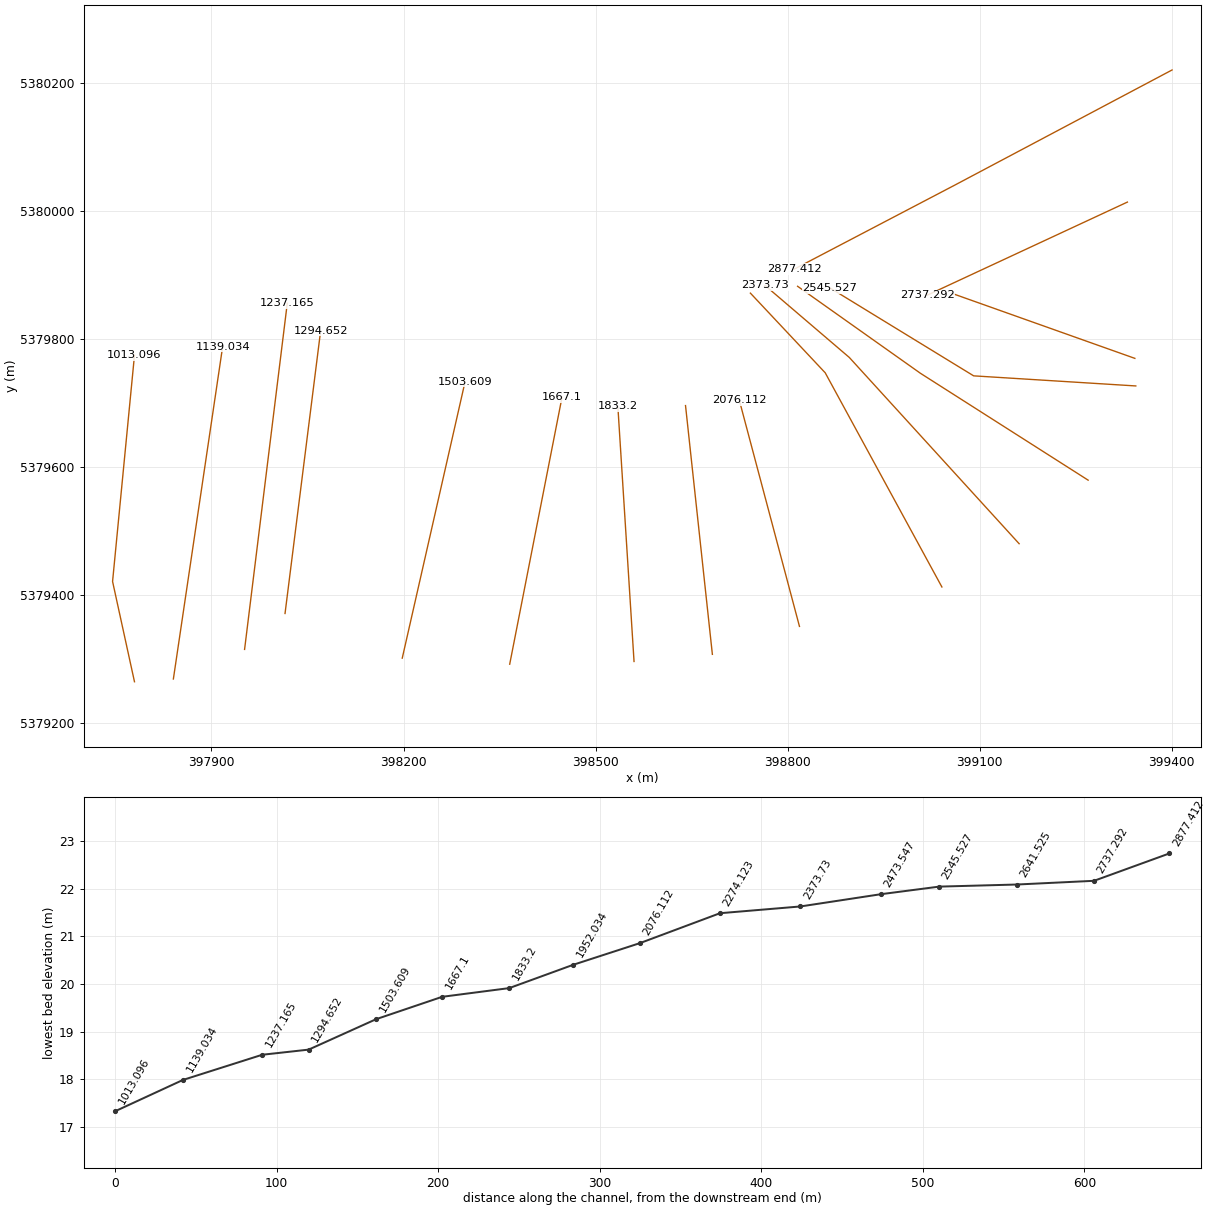
HEC-RAS study HarrysRiver.prj: Harry's River

--- HarrysRiver.g01 (geometry) --- (continued)

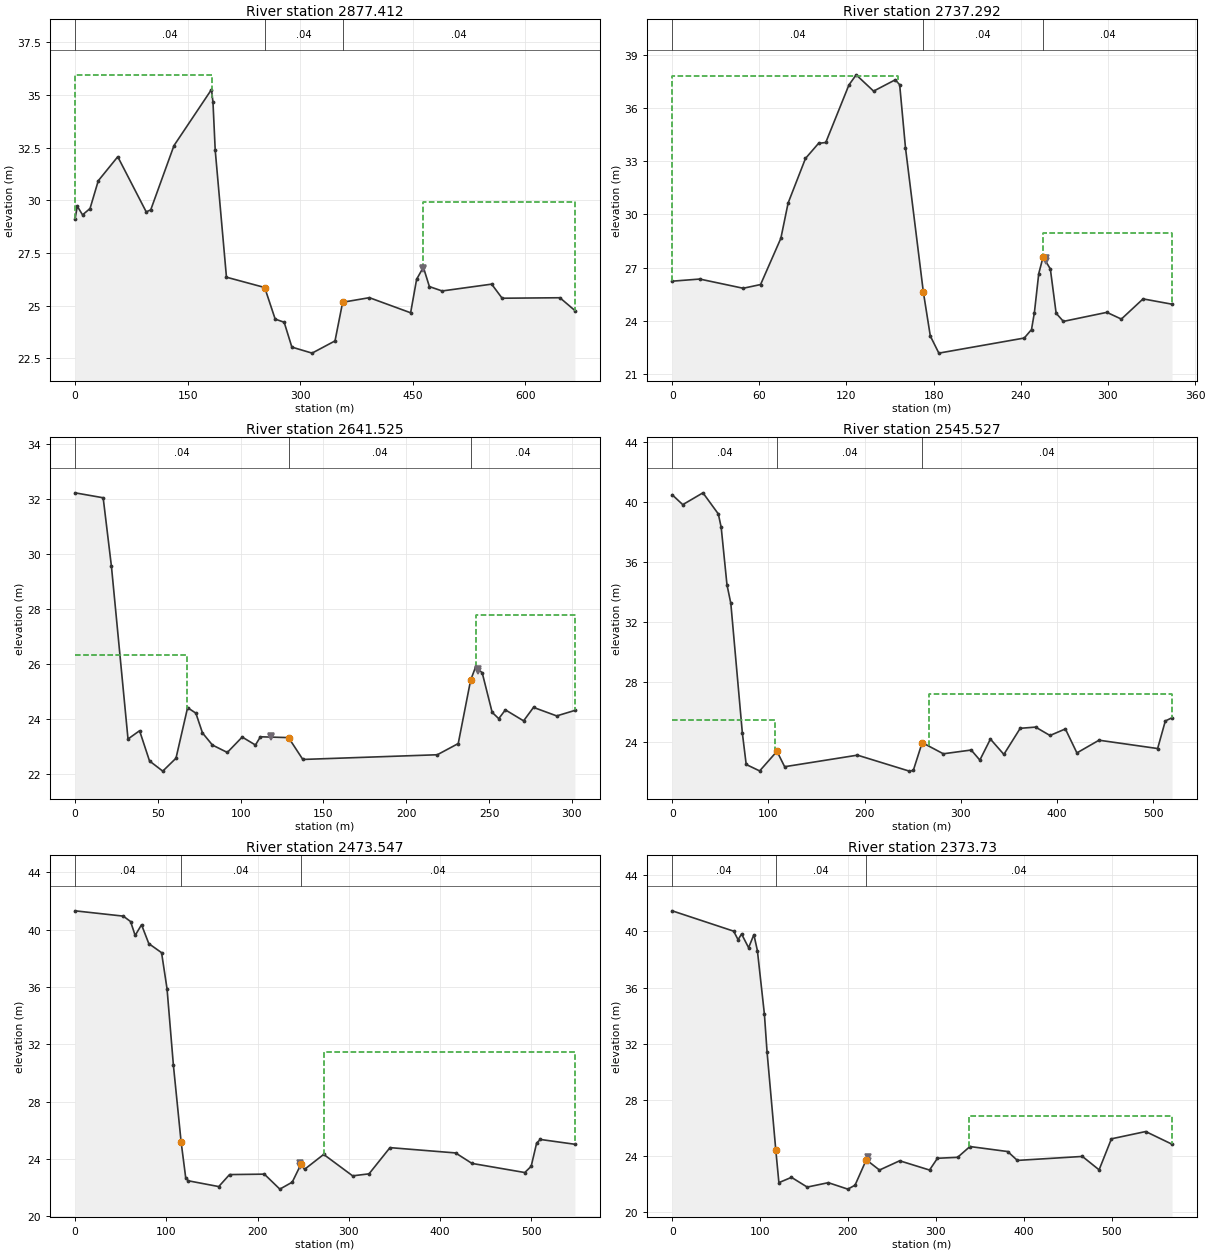
Type RM Length L Ch R = 1 ,2877.412,46.707,46.707,46.707
XS GIS Cut Line= 3
  399400.6030105 5380220.0941909  399060.5366006 5380039.8880591
  398810.5732566 5379909.0932861
#Sta/Elev= 30
       0    29.1       3   29.72    9.99   29.31   19.98   29.61   30.97   30.93
   56.95   32.07   94.91   29.45  100.91   29.55  131.88    32.6  181.83   35.26
  183.83   34.67  186.83   32.38  201.81   26.35  252.76   25.86  266.75   24.36
  278.74   24.21288.9811   23.03315.9212  22.744346.4918  23.324  356.67   25.16
 392.308  25.377 447.269   24.66 455.266  26.252 464.263  26.822 472.261  25.904
 489.255  25.696 555.234   26.02  569.23  25.351 646.206  25.374   666.2  24.768
#Mann= 3 , 0 , 0
       0     .04       0  252.76     .04       0  356.67     .04       0
Levee=0,,,-1,463.17,26.8,,Levee 9
#XS Ineff= 2 , 0
          183.17   35.96  463.17            29.9
Permanent Ineff=
       F       F
Bank Sta=252.76,356.67
XS Rating Curve= 0 ,0
Exp/Cntr=0.3,0.1

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
Type RM Length L Ch R = 1 ,2737.292,47.885,47.885,47.885
XS GIS Cut Line= 2
  399330.8457982 5380013.7291045  399018.3916182 5379868.4015789
#Sta/Elev= 30
       0   26.23   18.95   26.35   48.88   25.83   60.85   26.04   74.81   28.65
    79.8   30.64   91.77   33.16  100.75   34.01  105.73   34.06  121.69   37.31
  126.68   37.88  138.65   36.96  153.61    37.6  156.61   37.32   160.6   33.77
  172.92   25.61177.7095  23.134183.5834  22.168  242.39   23.02  247.38    23.5
  249.37   24.46  252.36   26.66  255.36    27.6  260.34   26.92  264.33   24.42
  269.32   23.96  299.25   24.47  309.22   24.09  324.18   25.23  344.13   24.93
#Mann= 3 , 0 , 0
       0     .04       0  172.92     .04       0  255.36     .04       0
Levee=0,,,-1,257.18,27.53,,Levee 9
#XS Ineff= 2 , 0
          155.42   37.79  255.02           28.95
Permanent Ineff=
       F       F
Bank Sta=172.92,255.36
XS Rating Curve= 0 ,0
Exp/Cntr=0.3,0.1

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
Type RM Length L Ch R = 1 ,2641.525,48,48,48
XS GIS Cut Line= 2
  399342.4720003 5379769.5788615  399056.1767748 5379871.3081295
#Sta/Elev= 30
       0   32.22   16.99   32.04   21.99   29.54   31.99   23.26   38.98   23.56
   44.98   22.46   52.98   22.09   60.97   22.56   67.97    24.4   72.97    24.2
   76.97   23.48   82.96   23.04   91.96   22.77  100.95   23.33  108.95   23.04
  111.95   23.34  128.94   23.31137.5623  22.515218.7839  22.686231.4134  23.094
  238.89    25.4  241.89   25.88  245.89   25.67  251.89   24.23  255.88      24
  259.88   24.32  270.88   23.92  276.87   24.41  290.87    24.1  301.86    24.3
#Mann= 3 , 0 , 0
       0     .04       0  128.94     .04       0  238.89     .04       0
Levee=-1,118.11,23.38,-1,243.3,25.72,Levee 11,Levee 9
#XS Ineff= 2 , 0
           67.84   26.33  242.07           27.79
Permanent Ineff=
       F       F
Bank Sta=128.94,238.89
XS Rating Curve= 0 ,0
Exp/Cntr=0.3,0.1

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
Type RM Length L Ch R = 1 ,2545.527,35.99,35.99,35.99
XS GIS Cut Line= 3
  399343.9380151 5379726.5010482  399090.6427777 5379742.2672355
  398866.2919034 5379879.5733624
#Sta/Elev= 30
       0    40.5   10.99   39.84   31.96   40.63   47.94   39.22   50.93   38.32
   56.92   34.49   60.92   33.25    72.9   24.59    76.9   22.49   90.88   22.06
  108.86   23.37  116.84   22.34192.4855  23.113246.3501  22.046250.5212  22.092
 259.747  23.951 281.714  23.204 310.671  23.455 319.657  22.783 330.641  24.186
  344.62  23.163 361.595  24.905 377.571  24.986 392.548  24.426 408.524  24.864
 420.506  23.263 443.472  24.111 504.381  23.555 512.369  25.395 519.359  25.612
#Mann= 3 , 0 , 0
       0     .04       0  108.86     .04       0 259.747     .04       0
#XS Ineff= 2 , 0
          106.78   25.46  266.43           27.21
Permanent Ineff=
       F       F
Bank Sta=108.86,259.747
XS Rating Curve= 0 ,0
Exp/Cntr=0.3,0.1

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
Type RM Length L Ch R = 1 ,2473.547,49.91,49.91,49.91
XS GIS Cut Line= 3
  399269.4920408 5379579.3205005  399007.6475816 5379746.1821662
  398815.6149126  5379882.187928
#Sta/Elev= 30
       0   41.31   52.91   40.94    60.9   40.56   65.89   39.59   72.88   40.34
   80.87   39.02   94.84   38.39  100.84   35.87  107.82   30.53  116.22   25.21
   121.3  22.681124.1415  22.469157.5064  22.065169.3416  22.902207.4888  22.933
224.4749  21.887238.0638  22.373   247.6   23.62  251.59   23.27  272.55   24.31
 304.264  22.814 322.235  22.954 345.198  24.783 417.081  24.413 435.052  23.682
 492.958  23.045 499.947   23.48 505.937  25.103 509.931  25.354  547.87  25.018
#Mann= 3 , 0 , 0
       0     .04       0  116.22     .04       0   247.6     .04       0
Levee=0,,,-1,246.87,23.72,,Levee 12
#XS Ineff= 2 , 0
                          272.78           31.46
Permanent Ineff=
       F       F
Bank Sta=116.22,247.6
XS Rating Curve= 0 ,0
Exp/Cntr=0.3,0.1

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
Type RM Length L Ch R = 1 ,2373.73 ,49.805,49.805,49.805
XS GIS Cut Line= 3
   399161.673735 5379480.0592033  398896.4064719  5379770.997491
  398764.8302908 5379883.4357535
#Sta/Elev= 30
       0   41.47   69.95   40.02   74.95   39.41   78.94   39.82   86.94   38.84
   92.93   39.77   96.93   38.64  104.92    34.1  107.92   31.42  117.91   24.39
121.4023  22.092135.7328  22.469153.6113  21.775177.6205  22.089199.8147  21.629
208.0399   21.91  220.84   23.72  235.83   22.99  258.81   23.65  292.79   22.99
 301.782  23.828 324.765  23.897 338.755  24.666 381.723  24.309 392.715  23.676
 466.715   23.96 485.715  23.004 499.715  25.215 538.715  25.735 568.715  24.829
#Mann= 3 , 0 , 0
       0     .04       0  117.91     .04       0  220.84     .04       0
Levee=0,,,-1,223.08,23.89,,Levee 12
#XS Ineff= 2 , 0
                           337.8           26.84
Permanent Ineff=
       F       F
Bank Sta=117.91,220.84
XS Rating Curve= 0 ,0
Exp/Cntr=0.3,0.1

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
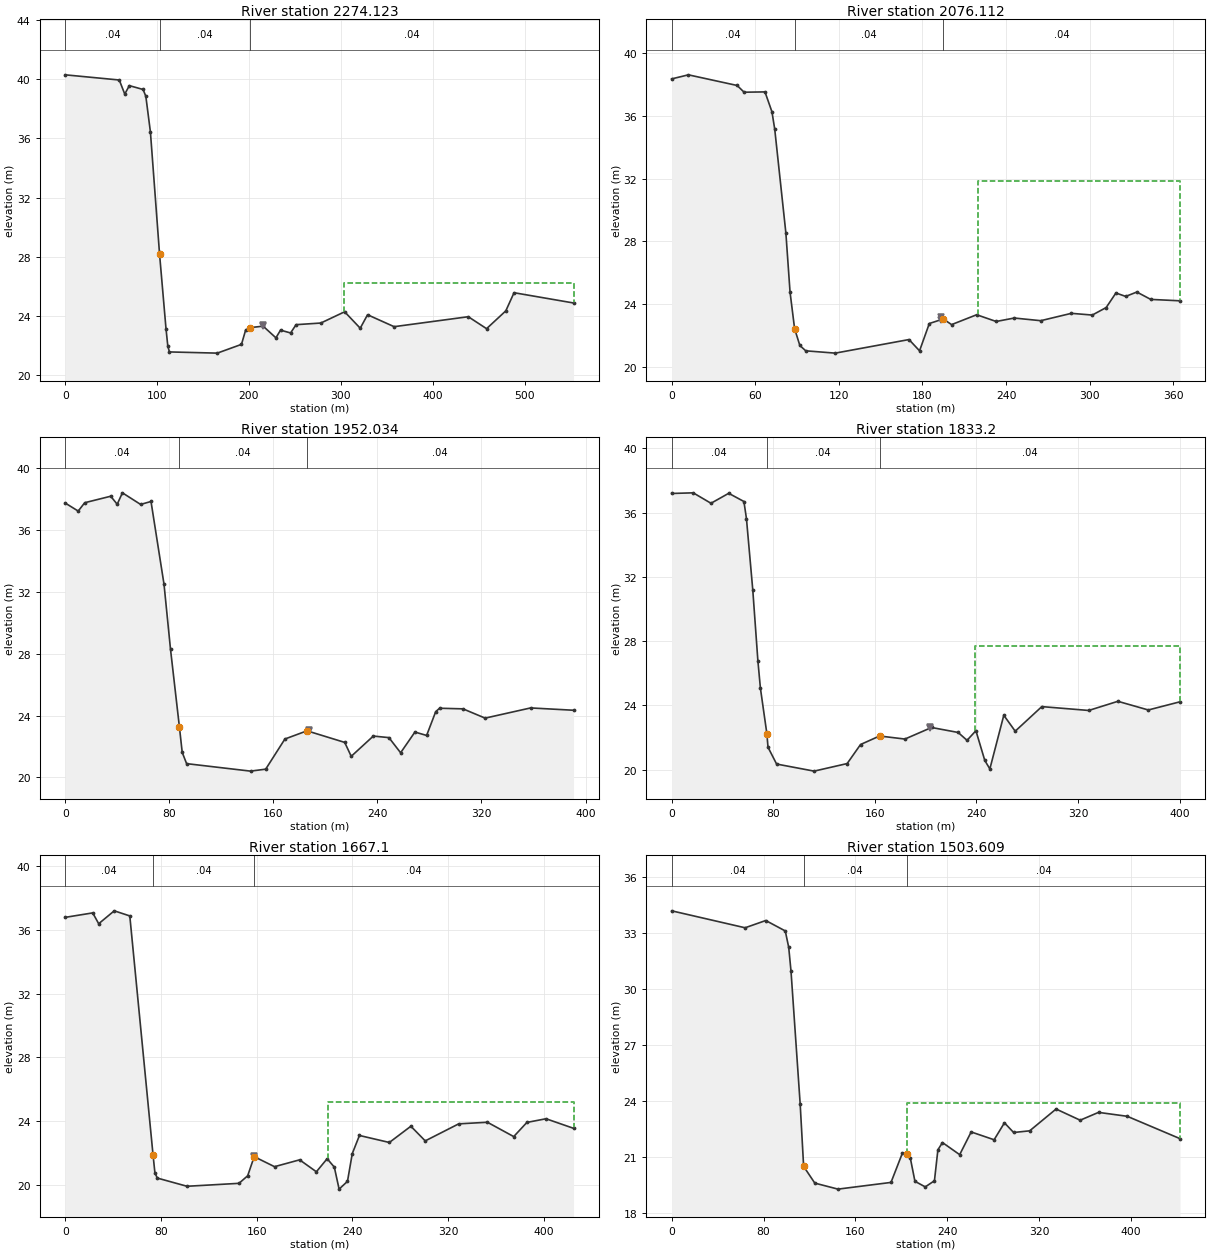
Type RM Length L Ch R = 1 ,2274.123,49.502,49.502,49.502
XS GIS Cut Line= 3
  399041.0199151 5379412.4588367   398858.755635 5379747.0378677
  398741.8863982 5379871.4899836
#Sta/Elev= 30
       0   40.29   58.85   39.94   64.83   38.99   69.82   39.56   84.78    39.3
   87.77   38.84   92.76   36.43  102.73   28.16  109.71   23.15  111.71  21.952
 113.484  21.568165.5603  21.487 191.897  22.079  196.49   23.06  201.47   23.21
  215.44   23.31   229.4   22.52  234.39   23.04  245.36   22.85  251.34   23.41
  278.27   23.52   304.2   24.28  321.16   23.17  329.14   24.08 358.062  23.274
 438.791  23.947 458.718  23.139 479.642  24.342 488.609  25.569 553.374  24.875
#Mann= 3 , 0 , 0
       0     .04       0  102.73     .04       0  201.47     .04       0
Levee=0,,,-1,215.15,23.38,,Levee 12
#XS Ineff= 2 , 0
                          303.44           26.23
Permanent Ineff=
       F       F
Bank Sta=102.73,201.47
XS Rating Curve= 0 ,0
Exp/Cntr=0.3,0.1

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
Type RM Length L Ch R = 1 ,2076.112,41.36,41.36,41.36
XS GIS Cut Line= 2
  398818.5376938 5379350.8483745  398724.4666977 5379704.5447938
#Sta/Elev= 30
       0   38.37      12   38.63   46.99   37.95   51.99   37.52   66.98   37.54
   71.98   36.27   73.98   35.16   81.98   28.53   84.98   24.75   88.24   22.42
92.00908  21.34796.25082  21.006117.4488  20.859170.3584  21.726177.9297  21.006
  184.95   22.75  194.95   23.04  200.94   22.68  218.94   23.31  232.94   22.88
  245.93    23.1  264.93   22.93  286.92    23.4  301.92   23.29  311.91   23.77
  318.91    24.7  325.91   24.48  333.91   24.76   343.9   24.29   364.9    24.2
#Mann= 3 , 0 , 0
       0     .04       0   88.24     .04       0  194.95     .04       0
Levee=0,,,-1,193.48,23.14,,Levee 12
#XS Ineff= 2 , 0
                          219.56           31.88
Permanent Ineff=
       F       F
Bank Sta=88.24,194.95
XS Rating Curve= 0 ,0
Exp/Cntr=0.3,0.1

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
Type RM Length L Ch R = 1 ,1952.034,39.61,39.61,39.61
XS GIS Cut Line= 2
  398682.4812593 5379307.2076312  398640.5400517 5379695.8251423
#Sta/Elev= 30
       0   37.74    9.99   37.22   14.99   37.76   34.98   38.18   39.97   37.66
   43.97    38.4   57.96   37.65   65.96   37.84   75.95   32.49   80.95   28.28
   87.77   23.27   89.94  21.61693.31545  20.887142.4398  20.403154.1098   20.53
  168.89   22.48  185.88   23.01  214.86   22.26  219.86   21.36  236.84   22.67
  248.84   22.57  257.83   21.59  268.82   22.93  277.82   22.71  284.81   24.25
  287.81   24.47   305.8   24.43  322.79   23.83  357.77   24.49  390.75   24.34
#Mann= 3 , 0 , 0
       0     .04       0   87.77     .04       0  185.88     .04       0
Levee=0,,,-1,187.14,23.08,,Levee 12
Bank Sta=87.77,185.88
XS Rating Curve= 0 ,0
Exp/Cntr=0.3,0.1

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
Type RM Length L Ch R = 1 ,1833.2  ,41.525,41.525,41.525
XS GIS Cut Line= 2
  398560.1160384   5379296.08352  398534.8142768 5379694.7351859
#Sta/Elev= 30
       0    37.2   16.97   37.24   30.95   36.59   44.92   37.21    56.9    36.7
    58.9   35.63   63.89   31.18   67.89   26.79   69.88   25.08   74.96   22.25
   75.87    21.482.63275  20.354112.1687  19.913138.2005  20.384  148.75   21.57
  163.73    22.1  183.69   21.91  204.66   22.63  225.62   22.32  232.61   21.83
   239.6   22.43  246.59   20.58  250.58   20.05  261.56   23.39  270.55    22.4
  291.51   23.93  328.45   23.69  351.41   24.26  375.37   23.72  400.33   24.23
#Mann= 3 , 0 , 0
       0     .04       0   74.96     .04       0  163.73     .04       0
Levee=0,,,-1,203.52,22.64,,Levee 12
#XS Ineff= 2 , 0
                          239.21           27.68
Permanent Ineff=
       F       F
Bank Sta=74.96,163.73
XS Rating Curve= 0 ,0
Exp/Cntr=0.3,0.1

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
Type RM Length L Ch R = 1 ,1667.1  ,40.873,40.873,40.873
XS GIS Cut Line= 2
  398365.8719457 5379291.8050166  398447.6177614 5379708.9046196
#Sta/Elev= 30
       0    36.8   22.99   37.08   27.98    36.4   40.98   37.21   53.97   36.89
    73.4   21.87   74.96   20.75   76.96  20.424 101.801  19.909145.1943  20.094
 152.459  20.568  157.91   21.77   174.9   21.14  195.88   21.57  209.87   20.82
  218.87   21.64  224.87   21.11  228.86   19.73  235.86   20.22  239.86   21.96
  245.85    23.1  270.84   22.66  288.83   23.68  300.82   22.76   328.8   23.83
  352.79   23.93  374.77   23.03  385.77   23.92  401.76   24.15  424.74   23.55
#Mann= 3 , 0 , 0
       0     .04       0    73.4     .04       0  157.91     .04       0
Levee=0,,,-1,157.71,21.81,,Levee 12
#XS Ineff= 2 , 0
                          219.38           25.21
Permanent Ineff=
       F       F
Bank Sta=73.4,157.91
XS Rating Curve= 0 ,0
Exp/Cntr=0.3,0.1

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
Type RM Length L Ch R = 1 ,1503.609,41.792,41.792,41.792
XS GIS Cut Line= 2
  398198.0177362 5379301.2609103   398296.113816 5379732.8836613
#Sta/Elev= 30
       0    34.2   63.96   33.29   81.95   33.68   98.94   33.12  101.94   32.24
  103.94   30.96  111.93   23.82  114.93   20.48124.6658  19.583144.8451   19.26
191.0315   19.62  200.88   21.18  204.88   21.17  207.88   20.92  211.88   19.68
  220.87   19.38  228.87   19.71  231.87   21.37  235.86   21.76  250.85   21.11
  260.85   22.33  280.84   21.91  289.83   22.82  297.83    22.3  311.82   22.39
  334.81   23.56  355.79   22.96  371.78   23.38  396.77   23.17  442.74   21.97
#Mann= 3 , 0 , 0
       0     .04       0  114.93     .04       0  204.88     .04       0
#XS Ineff= 2 , 0
                          204.85           23.91
Permanent Ineff=
       F       F
Bank Sta=114.93,204.88
XS Rating Curve= 0 ,0
Exp/Cntr=0.3,0.1

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
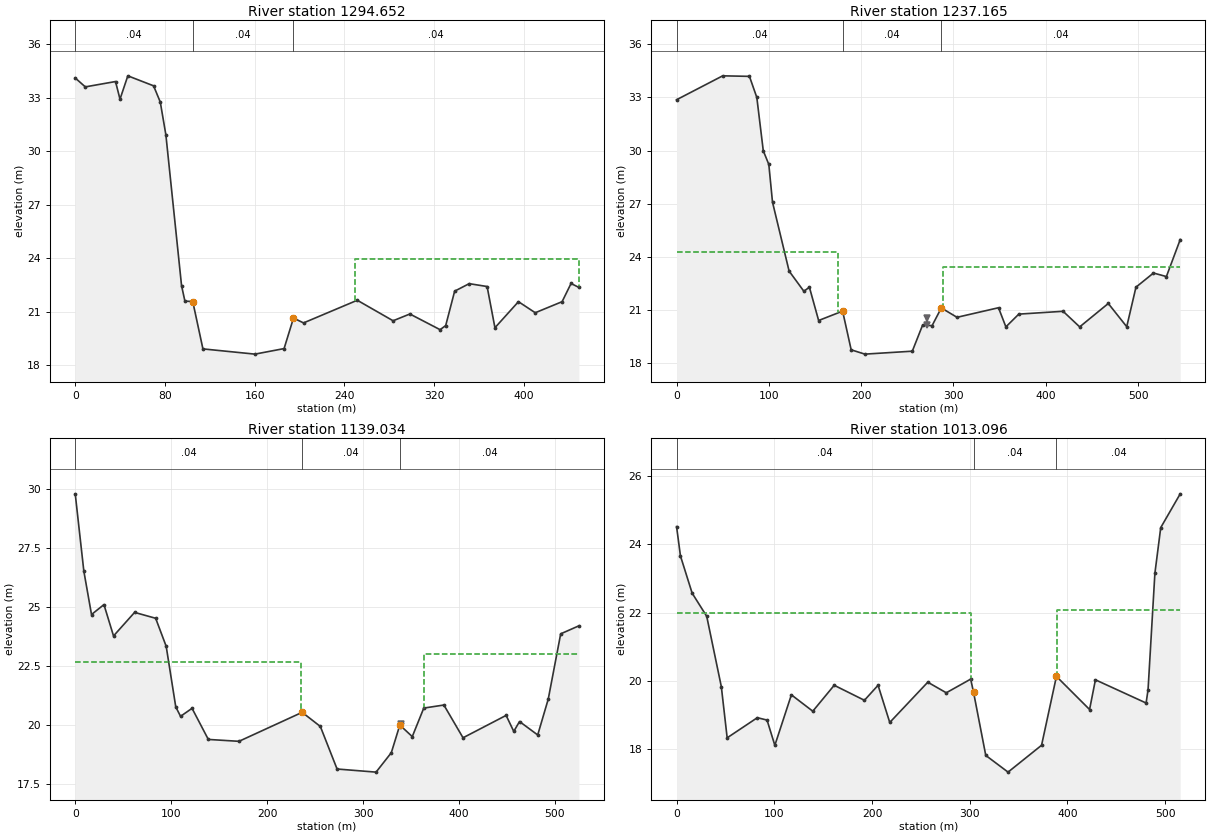
Type RM Length L Ch R = 1 ,1294.652,28.745,28.745,28.745
XS GIS Cut Line= 2
   398014.905054 5379371.0181226  398070.4928325 5379812.4504816
#Sta/Elev= 30
       0    34.1    8.98    33.6   35.93    33.9   39.92   32.91    46.9   34.22
   69.85   33.66   75.84   32.75   80.83   30.91    94.8   22.46    97.8   21.59
  104.78   21.57113.8585  18.913160.2477   18.62186.2172  18.931   194.6   20.64
  203.58   20.37  251.48   21.64  283.41   20.49  298.38   20.87  325.32   19.99
  330.31   20.22   338.3   22.15  351.27   22.57  367.24   22.41  374.22    20.1
  395.18   21.56  410.15   20.94   434.1   21.56  442.08   22.58  449.07   22.36
#Mann= 3 , 0 , 0
       0     .04       0  104.78     .04       0   194.6     .04       0
#XS Ineff= 2 , 0
                          249.34           23.96
Permanent Ineff=
       F       F
Bank Sta=104.78,194.6
XS Rating Curve= 0 ,0
Exp/Cntr=0.3,0.1

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
Type RM Length L Ch R = 1 ,1237.165,49.065,49.065,49.065
XS GIS Cut Line= 2
   397951.712736 5379314.9089385  398018.4078847 5379855.6206622
#Sta/Elev= 30
       0   32.87   49.97   34.22   78.95   34.19   86.94      33   93.94   29.99
   99.94   29.22  103.93   27.09  121.92    23.2  137.91   22.06  143.91   22.29
   153.9   20.41  179.88   20.94189.1625  18.755204.0379  18.512 255.389  18.678
  266.55   20.15  276.82   20.12  286.82   21.12  303.81   20.59  348.78   21.13
  356.77   20.05  370.76   20.77  418.73   20.93  436.72   20.05   467.7   21.37
  487.69   20.06  497.68   22.29  516.67   23.09  530.66   22.89  545.65   24.98
#Mann= 3 , 0 , 0
       0     .04       0  179.88     .04       0  286.82     .04       0
Levee=0,,,-1,271.72,20.56,,Levee 13
#XS Ineff= 2 , 0
          174.45    24.3  289.16           23.45
Permanent Ineff=
       F       F
Bank Sta=179.88,286.82
XS Rating Curve= 0 ,0
Exp/Cntr=0.3,0.1

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
Type RM Length L Ch R = 1 ,1139.034,41.98,41.98,41.98
XS GIS Cut Line= 2
  397840.4716759 5379268.7010899  397917.4847507 5379788.1115055
#Sta/Elev= 30
       0   29.79    8.98   26.51   16.97   24.67   29.95   25.09   39.93   23.76
   61.89   24.76   83.85   24.51   94.84   23.32  104.82   20.75  109.81   20.35
  121.79   20.69  138.76   19.37   170.7   19.29  236.59   20.52  255.56   19.92
272.9823  18.115313.6358  17.983329.5324  18.807  338.41   19.98  351.39   19.49
  363.37    20.7  384.33   20.83   404.3   19.44  449.22   20.39   457.2   19.71
  463.19   20.13  482.16   19.56  493.14   21.08  506.12   23.85  525.09   24.19
#Mann= 3 , 0 , 0
       0     .04       0  236.59     .04       0  338.41     .04       0
Levee=0,,,-1,339.38,20.02,,Levee 13
#XS Ineff= 2 , 0
          235.24   22.66  363.17           22.98
Permanent Ineff=
       F       F
Bank Sta=236.59,338.41
XS Rating Curve= 0 ,0
Exp/Cntr=0.3,0.1

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
Type RM Length L Ch R = 1 ,1013.096,37.743,37.743,37.743
XS GIS Cut Line= 3
  397779.7169151 5379264.4225864  397745.4888802 5379421.0158405
  397779.7169151 5379774.4202919
#Sta/Elev= 30
       0   24.52    3.98   23.66   15.93   22.57   30.86   21.89    45.8   19.83
   51.77   18.33   82.63   18.92   92.59   18.85  100.55   18.11  117.48   19.59
  139.38   19.11  161.29   19.87  192.21   19.43  206.17   19.87  218.14   18.78
  257.03   19.96  275.98   19.65  300.92   20.05  303.91   19.66316.3766  17.815
339.1816  17.325373.4651  18.112  388.68   20.13  422.59   19.16  428.58   20.03
  480.44   19.35  482.43   19.74  489.42   23.15   495.4   24.49  515.35   25.48
#Mann= 3 , 0 , 0
       0     .04       0  303.91     .04       0  388.68     .04       0
#XS Ineff= 2 , 0
          301.32   21.98   389.6           22.09
Permanent Ineff=
       F       F
Bank Sta=303.91,388.68
XS Rating Curve= 0 ,0
Exp/Cntr=0.3,0.1

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